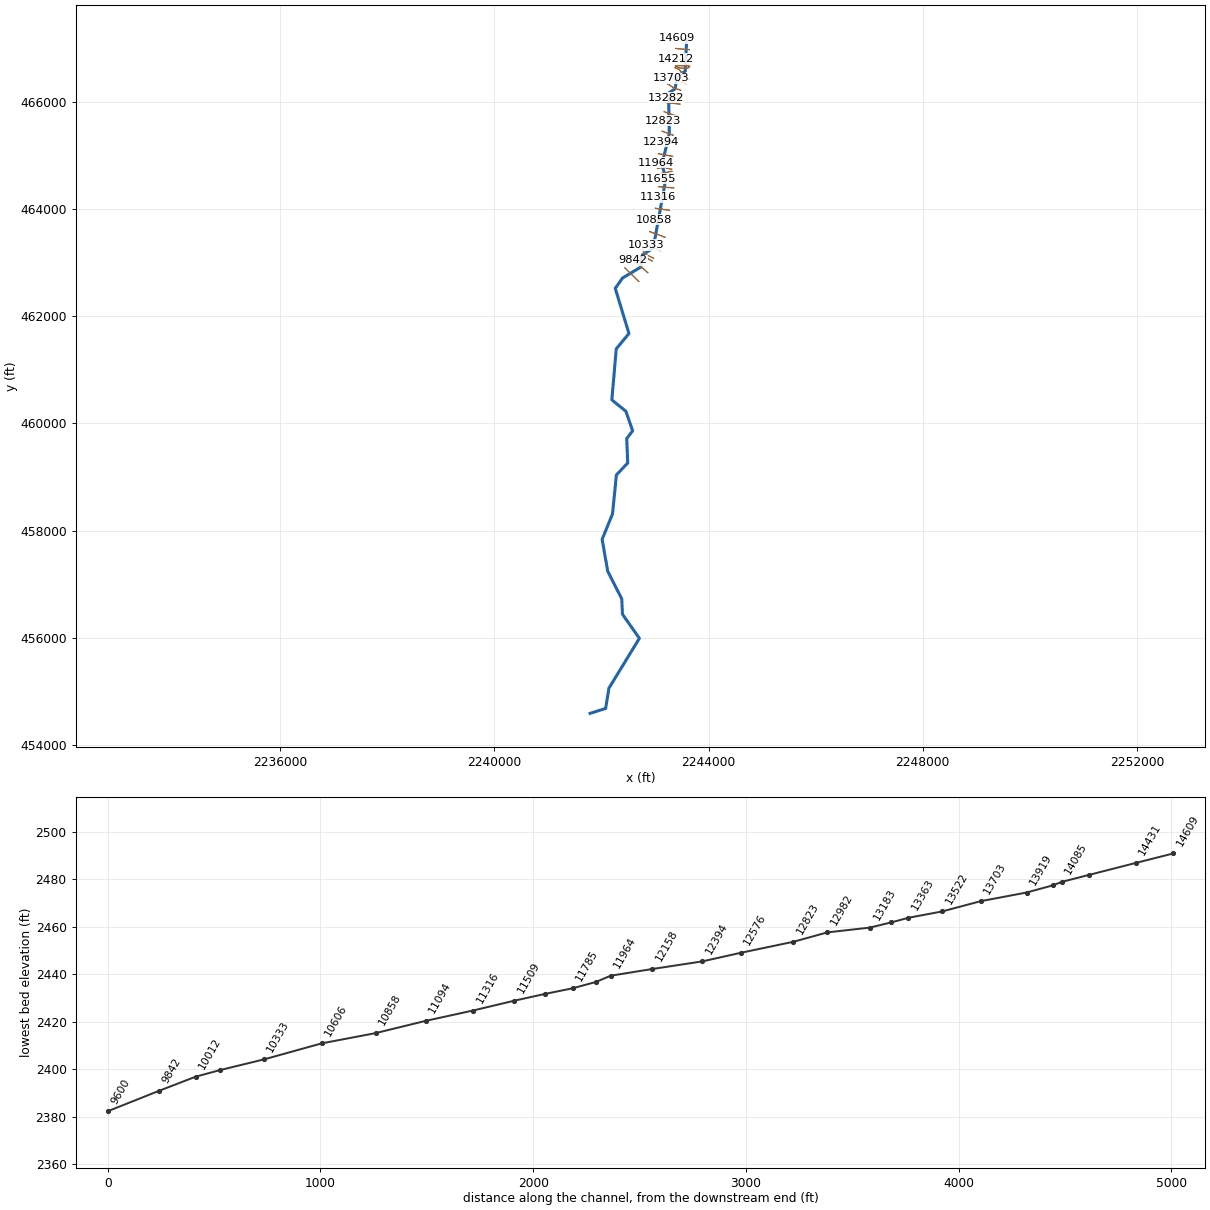
--- LWSLKRN.prj (project) ---

Proj Title=LWSLKRN
Current Plan=p01
Default Exp/Contr=0,0
English Units
Geom File=g01
Flow File=f01
Plan File=p01
Background Map Layer=Inundation Boundary (01pct Value_0)
BEGIN DESCRIPTION:
----------MODEL BY WOOD PLC 2021----------
Stream Name: Lewis Lick Run
Flood Zone: Enhanced Approximate
Pocahontas County, WV
HEC-RAS Version: RAS 6.1
Vertical Datum: NAVD88
Projection: NAD 1983 StatePlane West Virginia S FIPS 4702 (US Feet)
Terrain: 1-meter LIDAR (FEMA Region III 3DEP collected 2016-2018)
Land Use: 2019 NLCD
Hydrologic Method:
WV SIR2010-5033 regression equations
END DESCRIPTION:
DSS Export Rating Curves= 0
DSS Export Rating Curve Sorted= 0
DSS Export Volume Flow Curves= 0
DXF OffsetX= 0
DXF OffsetY= 0
DXF ScaleX= 0
DXF ScaleY= 0

--- LWSLKRN.p01 (plan) ---

Plan Title=Floodplain
Program Version=6.10
Short Identifier=Floodplain
Geom File=g01
Flow File=f01
Subcritical Flow
K Sum by GR= 0
Std Step Tol= 0.01
Critical Tol= 0.01
Num of Std Step Trials= 20
Max Error Tol= 0.3
Flow Tol Ratio= 0.001
Split Flow NTrial= 30
Split Flow Tol= 0.02
Split Flow Ratio= 0.02
Log Output Level= 0
Friction Slope Method= 1
Unsteady Friction Slope Method= 2
Unsteady Bridges Friction Slope Method= 1
Parabolic Critical Depth
Global Vel Dist= 0 , 0 , 0
Global Log Level= 0
CheckData=True
Encroach Param=-1 ,0,0, 0
Mapping Interval=1HOUR
Computation Time Step Use Courant=        0
Computation Time Step Use Time Series=    0
Computation Time Step Count To Double=0
Computation Time Step Max Doubling=0
Computation Time Step Max Halving=0
Computation Time Step Residence Courant=0
Run HTab= 0
Run UNet= 0
Run Sediment= 0
Run PostProcess= 0
Run WQNet= 0
Run RASMapper=-1
UNET Theta= 0
UNET Theta Warmup= 0
UNET ZTol= 0
UNET ZSATol= 0
UNET MxIter= 0
UNET Max Iter WO Improvement= 0
UNET MaxInSteps= 0
UNET DtIC= 0
UNET DtMin= 0
UNET MaxCRTS= 0
UNET WFStab= 0
UNET SFStab= 0
UNET WFX= 1
UNET SFX= 1
UNET Gravity=32.174
UNET 1D Methodology=Finite Difference
UNET DSS MLevel= 1
UNET Pardiso=0
UNET DZMax Abort= 0
UNET Use Existing IB Tables= 0
UNET Froude Reduction=False
UNET Froude Limit= 0
UNET Froude Power= 0
UNET D1 Cores= 0
UNET WindReference=Eulerian
UNET WindDragFormulation=Hsu (1988)
UNET D2 Coriolis=0
UNET D2 Cores= 0
UNET D2 Theta= 1
UNET D2 Theta Warmup= 1
UNET D2 Z Tol= 0.01
UNET D2 Volume Tol= 0.01
UNET D2 Max Iterations= 20
UNET D2 Equation= 0
UNET D2 RampUpFraction=0.1
UNET D2 TimeSlices= 1
UNET D2 Turbulence Formulation=Non-Conservative (original)
UNET D2 Eddy Viscosity=0.3
UNET D2 Transverse Eddy Viscosity=0.1
UNET D2 Smagorinsky Mixing=0
UNET D2 BCVolumeCheck=0
UNET D2 Cores=0
UNET D2 SolverType=PARDISO (Direct)
UNET D2 Minimum Iterations= 2147483647
UNET D2 Maximum Iterations= 2147483647
UNET D2 Restart Number= 10
UNET D2 Relaxation Coeff=1.3
UNET D2 SOR Precondition Iterations= 10
UNET D2 ILUT Maximum Fill= 8
UNET D2 ILUT Tolerance=1E-08
UNET D1D2 MaxIter= 0
UNET D1D2 ZTol=0.01
UNET D1D2 QTol=0.1
UNET D1D2 MinQTol=1
Write IC File= 0
Write IC File at Fixed DateTime=0
Write IC File at Sim End=0
Echo Input=False
Echo Parameters=False
Echo Output=False
Write Detailed= 0
HDF Write Warmup=0
HDF Write Time Slices=0
HDF Flush=0
HDF Compression= 1
HDF Chunk Size= 1
HDF Spatial Parts= 1
HDF Use Max Rows=0
HDF Fixed Rows= 1
Calibration Method= 0
Calibration Iterations= 20
Calibration Max Change=0.05
Calibration Tolerance=0.2
Calibration Maximum=1.5
Calibration Minimum=0.5
Calibration Optimization Method= 1
WQ AD Non Conservative
WQ ULTIMATE=-1
WQ Max Comp Step=1HOUR
WQ Output Interval=15MIN
WQ Output Selected Increments= 0
WQ Output face flow=0
WQ Output face velocity=0
WQ Output face area=0
WQ Output face dispersion=0
WQ Output cell volume=0
WQ Output cell surface area=0
WQ Output cell continuity=0
WQ Output cumulative cell continuity=0
WQ Output face conc=0
WQ Output face dconc_dx=0
WQ Output face courant=0
WQ Output face peclet=0
WQ Output face adv mass=0
WQ Output face disp mass=0
WQ Output cell mass=0
WQ Output cell source sink temp=0
WQ Output nsm pathways=0
WQ Output nsm derived pathways=0
WQ Create Restart=0
WQ Fixed Restart=0
WQ System Summary=0
WQ Write To DSS=0
Sorting and Armoring Iterations= 10
XS Update Threshold= 0.02
Bed Roughness Predictor= 0
Hydraulics Update Threshold= 0.02
Energy Slope Method= 1
Volume Change Method= 1
Sediment Retention Method= 0
Sediment TS Multiplier= 1
Warm Up Method= 0
XS Weighting Method= 0
Number of US Weighted Cross Sections= 1
Number of DS Weighted Cross Sections= 1
Upstream XS Weight=0
Main XS Weight=1
Downstream XS Weight=0
Number of DS XS's Weighted with US Boundary= 1
Upstream Boundary Weight= 1
Weight of XSs Associated with US Boundary= 0
Number of US XS's Weighted with DS Boundary= 1
Downstream Boundary Weight= 0.5
Weight of XSs Associated with DS Boundary= 0.5
Percentile Method= 0
Sediment Output Level= 3
Mass or Volume Output= 0
Output Increment Type= 1
Profile and TS Output Increment= 1
Transport Output Increment 1
XS Output Flag= 0
XS Output Increment= 10
Read HDF5 Sediment Hotstart= 0
Sediment Hotstart Type= 0
Write Gradation File= 0
Read Gradation Hotstart= 0
Write HDF5 File= 1
Write Binary Output= 1
Write DSS Sediment File= 0
DSS Sediment Output Type= 1
SV Curve= 0
Specific Gage Flag= 0
Subcell Erosion Methods= 0
Subcell Deposition Methods= 0
Advection Scheme= 1
Matrix Solver= 0
Implicit Weighting Factor= 1
Maximum Outer Loop Convergence Iterations= 5
Convergence Maximum Absolute= 0.001
Convergence RMSE= 0.0001
Grain Fractions Max Abs Error= 0.001
Max Subgrid Regions= 1
Max Subgrid Length Scale= 3.402823E+38
Initial Layer Thickness= 3.402823E+38
Min Layer Thickness= 3.402823E+38
Max Layer Thickness= 3.402823E+38
Number of Layers= 5

--- LWSLKRN.f01 (steady flow) ---

Flow Title=Flow
Program Version=6.10
Number of Profiles= 6
Profile Names=01pct,10pct,04pct,02pct,0_2pct,01plus
River Rch & RM=LWSLKRN,Main            ,14609
     648     344     457     549     903     959
River Rch & RM=LWSLKRN,Main            ,6886
     811     434     574     688    1120    1200
Boundary for River Rch & Prof#=LWSLKRN,Main            , 1
Up Type= 0
Dn Type= 3
Dn Slope=0.02277
Boundary for River Rch & Prof#=LWSLKRN,Main            , 2
Up Type= 0
Dn Type= 3
Dn Slope=0.02277
Boundary for River Rch & Prof#=LWSLKRN,Main            , 3
Up Type= 0
Dn Type= 3
Dn Slope=0.02277
Boundary for River Rch & Prof#=LWSLKRN,Main            , 4
Up Type= 0
Dn Type= 3
Dn Slope=0.02277
Boundary for River Rch & Prof#=LWSLKRN,Main            , 5
Up Type= 0
Dn Type= 3
Dn Slope=0.02277
Boundary for River Rch & Prof#=LWSLKRN,Main            , 6
Up Type= 0
Dn Type= 3
Dn Slope=0.02277
DSS Import GetInterval= 0
DSS Import GetPeak= 0
DSS Import FillOption= 0

--- LWSLKRN.g01 (geometry) ---

Geom Title=Geometry
Program Version=6.10

River Reach=LWSLKRN         ,Main
Reach XY= 30
     2243590.444      467168.238     2243565.345      466584.928
     2243404.715      466476.3842243377.77549518 466255.94175076
2243252.51249491466171.1026211862243266.70178068465418.102393978
2243130.89174874464839.129100681     2243201.735      464573.803
     2242966.766      463276.409     2242763.637      463150.379
     2242730.436       462919.922242394.37601998 462718.38640521
2242257.56114796462524.742696965     2242513.301        461681.2
     2242276.049      461393.654     2242193.869      460441.288
2242456.14166065460228.0361016382242582.20133404459862.598055439
2242471.85475878459719.7608275642242490.05114308459261.736877888
2242278.83027872459037.961472829     2242206.369      458310.155
     2242012.508      457835.4742242116.99166397457239.492080973
2242379.30590521456722.084083497     2242392.318      456435.682
     2242708.242      455985.424      2242138.73      455052.728
2242078.63143476 454675.27269572     2241786.941      454583.312

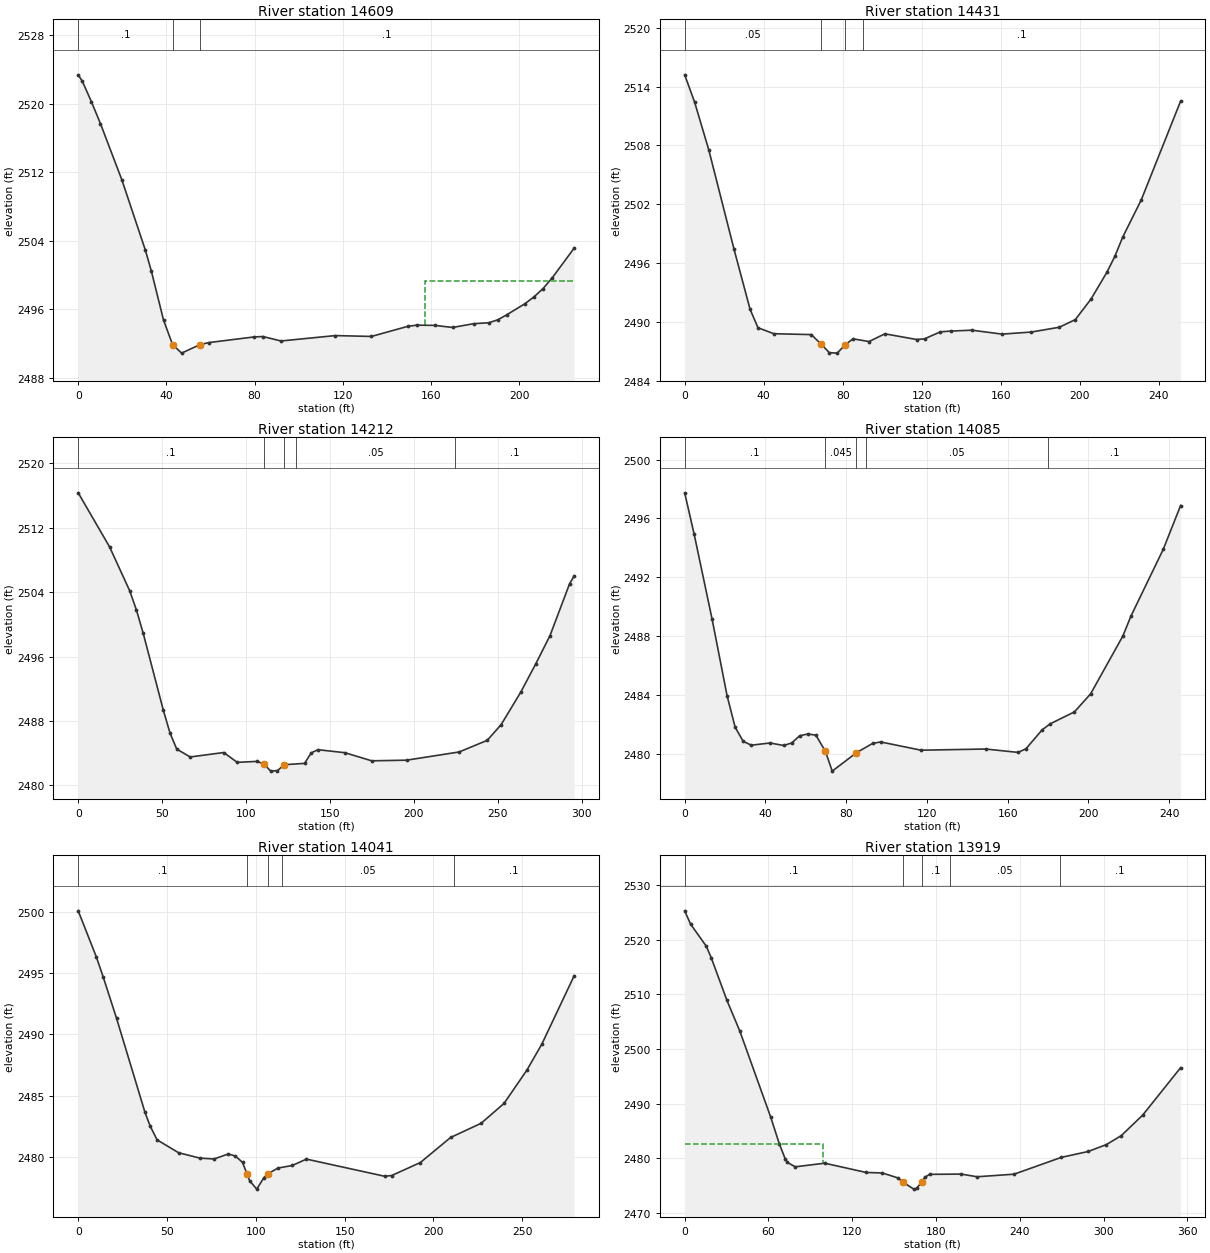
Type RM Length L Ch R = 1 ,14609   ,176,178.1,178.8
XS GIS Cut Line= 2
2243633.98920593467147.399369476 2243414.4413015467196.414715582
#Sta/Elev= 30
       0 2523.37     1.9  2522.6       6 2520.22    10.1 2517.66    19.8  2511.1
    30.5 2502.86    33.2 2500.42    38.7 2494.72    42.8 2491.85    46.9 2490.85
    55.1 2491.83    59.2 2492.08    79.7 2492.74    83.8 2492.79      92 2492.27
   116.6  2492.9     133  2492.8   149.4 2493.97   153.5 2494.12   161.7 2494.09
   169.9 2493.85   179.4 2494.29   186.3  2494.4   190.4 2494.75   194.5 2495.34
   202.7 2496.63   206.8 2497.43   210.9  2498.4     215 2499.63     225 2503.12
#Mann= 3 ,-1,0
       0      .1       0    42.8    .045       0    55.1      .1       0
#XS Ineff= 2 , 0
                          157.46         2499.25
Permanent Ineff=
       F       F
Bank Sta=42.8,55.1
XS Rating Curve= 0 ,0
Exp/Cntr(USF)=0,0
Exp/Cntr=0.3,0.1

Type RM Length L Ch R = 1 ,14431   ,217.4,219.9,220.3
XS GIS Cut Line= 2
2243641.13727724466985.0360354982243390.95478149467005.459096376
#Sta/Elev= 30
       0  2515.2       5 2512.43    12.2 2507.54      25 2497.39    33.1 2491.28
    37.1  2489.4    45.1 2488.79    64.1  2488.7    69.2  2487.7    73.2 2486.86
    77.2 2486.81    81.2 2487.66    85.2 2488.27    93.3 2487.99   101.3 2488.78
   117.4  2488.2   121.4 2488.27   129.4 2488.98   134.6 2489.06   145.4 2489.15
   160.6 2488.75   175.4 2488.96   189.6 2489.45   197.7 2490.23   205.6 2492.31
   213.7 2495.06   217.7 2496.68   221.7 2498.65   231.1 2502.45     251 2512.52
#Mann= 4 ,-1,0
       0     .05       0    69.2    .045       0    81.2     .05       0
      90      .1       0
Bank Sta=69.2,81.2
XS Rating Curve= 0 ,0
Exp/Cntr(USF)=0,0
Exp/Cntr=0.3,0.1

Type RM Length L Ch R = 1 ,14212   ,126.4,126.9,124.7
XS GIS Cut Line= 3
2243674.83532769466799.928688357 2243450.6625092466791.271071986
  2243382.268975466810.583724317
#Sta/Elev= 30
       0 2516.34    18.7 2509.62    30.7 2504.16    34.7 2501.77    38.7 2498.91
    50.7 2489.34    54.7  2486.5    58.7 2484.51    66.7 2483.54    86.7 2484.09
    94.7 2482.87   106.7 2482.99   110.7 2482.64   114.7 2481.78   118.7 2481.85
   122.8 2482.58   134.8 2482.74   138.8 2484.05   142.8 2484.44   158.8 2484.07
   174.8 2483.06   195.6 2483.14   226.9 2484.16   243.6  2485.6   251.9 2487.55
   263.6 2491.59   272.6 2495.13     281  2498.6   292.7 2505.06   295.4 2506.02
#Mann= 5 ,-1,0
       0      .1       0   110.7    .045       0   122.8      .1       0
     130     .05       0  224.34      .1       0
Bank Sta=110.7,122.8
XS Rating Curve= 0 ,0
Exp/Cntr(USF)=0,0
Exp/Cntr=0.3,0.1

Type RM Length L Ch R = 1 ,14085   ,43.5,43.7,44.4
XS GIS Cut Line= 2
2243633.20758974 466681.44298362 2243387.5422096466687.112184701
#Sta/Elev= 30
       0 2497.74     4.7 2494.93    13.6 2489.16      21 2483.98      25 2481.84
      29 2480.88      33 2480.62    42.3 2480.77      49  2480.6      53 2480.77
      57 2481.26      61 2481.38      65  2481.3   69.722480.204    73.1 2478.86
    85.1 2480.11    93.1 2480.74    97.1 2480.84   117.1 2480.28   149.1 2480.36
   165.2 2480.13   169.1 2480.38   177.1 2481.66   181.1 2482.07   193.1 2482.88
   201.1  2484.1   217.1 2488.03   221.1 2489.38   237.1 2493.91   245.7 2496.88
#Mann= 5 ,-1,0
       0      .1       0   69.72    .045       0    85.1      .1       0
      90     .05       0     180      .1       0
Bank Sta=69.72,85.1
XS Rating Curve= 0 ,0
Exp/Cntr(USF)=0,0
Exp/Cntr=0.3,0.1

Type RM Length L Ch R = 1 ,14041   ,130.7,122.2,113.2
XS GIS Cut Line= 4
2243647.34900555466671.2136425432243615.88493955466639.324386467
 2243469.1943616466640.1747666292243387.13267596466671.213642543
#Sta/Elev= 30
       0 2500.07    10.2 2496.31    14.1 2494.66    21.6 2491.29    37.6 2483.62
    40.5 2482.51    44.4 2481.38    56.5 2480.33    68.5 2479.89    76.5 2479.82
    84.5 2480.23    88.5 2480.06    92.5 2479.54   95.142478.557    96.5 2478.05
   100.5 2477.36   104.5 2478.29     107 2478.63   112.5 2479.08   120.5 2479.29
   128.5 2479.81   172.5 2478.41   176.5 2478.47   192.6 2479.53   209.7 2481.58
   226.8 2482.73   239.7 2484.35   252.5 2487.05     261 2489.19   279.2 2494.77
#Mann= 5 ,-1,0
       0      .1       0   95.14    .045       0     107      .1       0
   114.8     .05       0  211.49      .1       0
Bank Sta=95.14,107
XS Rating Curve= 0 ,0
Exp/Cntr(USF)=0,0
Exp/Cntr=0.3,0.1

Type RM Length L Ch R = 1 ,13919   ,205.8,215.5,218.7
XS GIS Cut Line= 4
2243639.15936713466421.2554231082243448.96553825466611.027811572
2243436.16563631466620.7178590912243370.98041155466647.452642627
#Sta/Elev= 30
       0 2525.25     4.2 2522.83    15.5 2518.77      19 2516.69    30.3 2508.86
    39.5 2503.26    61.5 2487.62    67.8 2482.65      72 2479.91    73.5 2479.27
    79.2 2478.46   100.3 2479.12   130.1 2477.42   141.5 2477.34   152.8 2476.42
   156.62475.611   164.1 2474.38   166.1 2474.53   169.8 2475.68   171.8 2476.51
   175.4 2477.08   198.1 2477.13   209.4 2476.64   235.9 2477.11   269.7 2480.18
     289 2481.26     302 2482.52   312.7 2484.16     328  2487.9   355.2 2496.58
#Mann= 5 ,-1,0
       0      .1       0   156.6    .045       0   169.8      .1       0
     190     .05       0  268.68      .1       0
#XS Ineff= 2 , 0
           99.11 2482.68
Permanent Ineff=
       F       F
Bank Sta=156.6,169.8
XS Rating Curve= 0 ,0
Exp/Cntr(USF)=0,0
Exp/Cntr=0.3,0.1

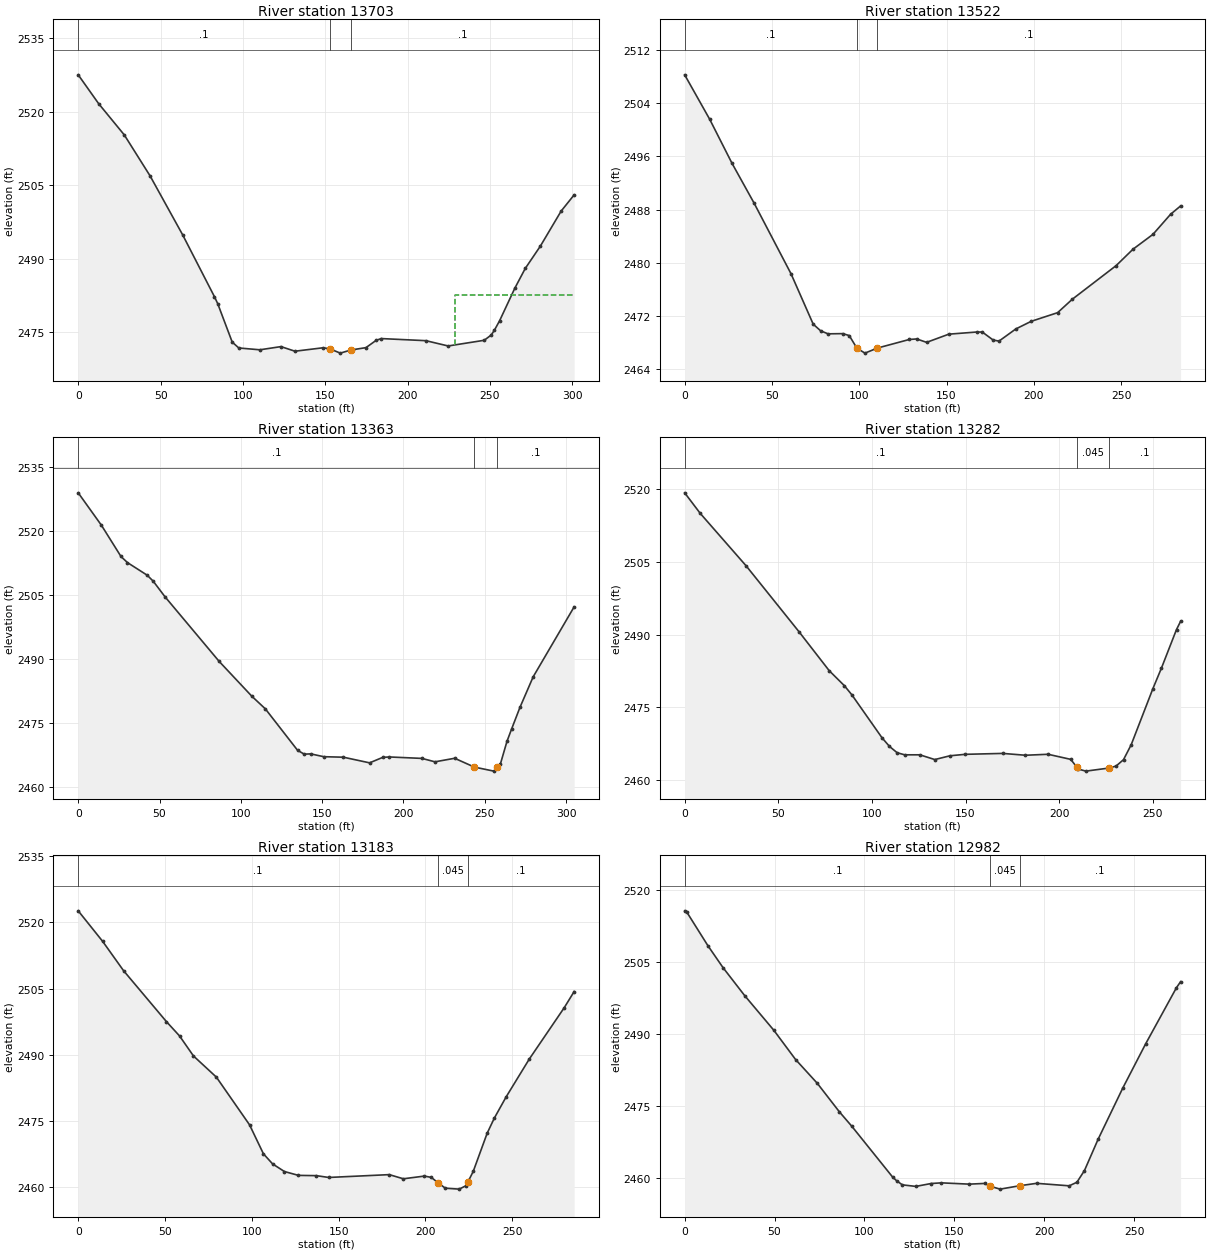
Type RM Length L Ch R = 1 ,13703   ,178.9,180.6,180
XS GIS Cut Line= 2
2243575.78348243466348.8576891592243292.92408927466451.994146591
#Sta/Elev= 30
       0 2527.52    12.4 2521.64      28 2515.25    43.6 2506.92    63.4 2494.88
    82.7 2482.26    84.7 2480.83    93.5 2472.99    97.5 2471.79   110.3 2471.42
   123.1 2472.07   131.6 2471.13   148.6 2471.83   152.7 2471.63   159.1 2470.74
   165.6 2471.38   174.7 2471.86   180.9 2473.35     184 2473.71   211.1 2473.28
   224.6  2472.2   246.5 2473.36   250.8 2474.45   252.7 2475.43   255.8 2477.32
   265.1    2484   271.4 2488.01   280.6 2492.58   293.2 2499.72   301.1 2503.03
#Mann= 3 ,-1,0
       0      .1       0   152.7    .045       0   165.6      .1       0
#XS Ineff= 2 , 0
                          228.49         2482.59
Permanent Ineff=
       F       F
Bank Sta=152.7,165.6
XS Rating Curve= 0 ,0
Exp/Cntr(USF)=0,0
Exp/Cntr=0.3,0.1

Type RM Length L Ch R = 1 ,13522   ,151.1,159.3,157.8
XS GIS Cut Line= 3
2243477.75378755466226.895285286  2243346.779311 466272.16294731
2243225.39023732466352.338390797
#Sta/Elev= 30
       0 2508.25   14.37 2501.55   27.06 2494.98   39.76 2488.97   60.92 2478.35
   73.62 2470.78   77.85 2469.79   82.08 2469.33   90.55 2469.36   94.25 2469.07
   98.63 2467.18  103.24 2466.43   110.42467.192  128.64 2468.48  132.87 2468.56
  138.58 2468.05  151.29 2469.28  167.17  2469.6  170.46  2469.6  176.71 2468.39
  180.05 2468.24  189.64 2470.06  198.48 2471.21   213.6 2472.51  222.02 2474.53
  247.16 2479.59  256.75 2482.04  268.22 2484.28  278.32  2487.3  284.05 2488.55
#Mann= 3 ,0,0
       0      .1       0   98.63    .045       0   110.4      .1       0
Bank Sta=98.63,110.4
XS Rating Curve= 0 ,0
Exp/Cntr(USF)=0,0
Exp/Cntr=0.3,0.1

Type RM Length L Ch R = 1 ,13363   ,80.5,81,79.7
XS GIS Cut Line= 2
2243506.34507544466144.6270803822243203.06262141466177.303977786
#Sta/Elev= 30
       0 2528.92    14.3 2521.31    26.3 2514.01    30.3 2512.58    42.4 2509.63
    46.1 2508.24    53.3 2504.61    86.7 2489.43   106.8 2481.27   115.1 2478.32
   134.9 2468.62     139 2467.72     143 2467.78     151 2467.12   163.1    2467
   179.2 2465.68   187.2 2466.95   191.2 2467.06   211.4 2466.72   219.4 2465.92
   231.5 2466.75   243.6 2464.69   255.6 2463.74  257.692464.603   259.7 2465.49
   263.7 2470.73   266.5 2473.57   271.7  2478.7   279.8 2485.83     305 2502.22
#Mann= 3 ,-1,0
       0      .1       0   243.6    .045       0  257.69      .1       0
Bank Sta=243.6,257.69
XS Rating Curve= 0 ,0
Exp/Cntr(USF)=0,0
Exp/Cntr=0.3,0.1

Type RM Length L Ch R = 1 ,13282   ,99.5,99.5,99.6
XS GIS Cut Line= 3
2243472.75430676466064.471575513 2243236.1842576466094.347689969
2243209.96644287 466090.68939024
#Sta/Elev= 30
       0 2519.29     8.3 2515.05    32.8 2504.22    61.1 2490.58    77.2 2482.55
    85.3 2479.45    89.3 2477.56   105.4 2468.69   109.4  2466.9   113.5  2465.6
   117.5 2465.17   125.6 2465.17   133.6 2464.19   141.7 2464.97   149.8 2465.27
   169.9 2465.46     182 2465.08   194.1 2465.28   206.2 2464.23   209.62462.552
   210.2 2462.23   214.3  2461.8   226.7 2462.44   230.4 2462.84   234.4 2464.17
   238.5 2467.25   250.1 2478.85   254.6 2483.03   262.7 2491.05   264.9 2492.75
#Mann= 3 ,-1,0
       0      .1       0   209.6    .045       0   226.7      .1       0
Bank Sta=209.6,226.7
XS Rating Curve= 0 ,0
Exp/Cntr(USF)=0,0
Exp/Cntr=0.3,0.1

Type RM Length L Ch R = 1 ,13183   ,205.3,200.8,199.4
XS GIS Cut Line= 2
2243466.13738835465966.6228755012243182.48376505466000.661310298
#Sta/Elev= 30
       0  2522.6    14.1 2515.68    26.1 2509.07    50.8 2497.54    58.4 2494.28
    66.4 2489.76    79.6 2484.97    98.7 2474.18   106.7 2467.62     112 2465.33
   118.8 2463.61   126.9 2462.74   137.2 2462.68   144.3 2462.27   179.2 2462.91
   187.3 2461.97   199.4 2462.58   203.4 2462.29   207.4 2461.03   211.5 2459.84
   219.5 2459.63   223.6 2460.45  224.562461.282   227.6 2463.68   235.6 2472.29
   239.7 2475.69   246.5 2480.49   259.8 2489.03     280 2500.69   285.7 2504.34
#Mann= 3 ,-1,0
       0      .1       0   207.4    .045       0  224.56      .1       0
Bank Sta=207.4,224.56
XS Rating Curve= 0 ,0
Exp/Cntr(USF)=0,0
Exp/Cntr=0.3,0.1

Type RM Length L Ch R = 1 ,12982   ,152.4,159.1,161.6
XS GIS Cut Line= 3
2243433.23356804465747.6422783132243348.13748105465760.123037738
2243170.00300562465825.930678344
#Sta/Elev= 30
       0 2515.63     1.1 2515.41    12.9 2508.37    21.3  2503.8    33.4 2497.94
    49.6 2490.72    61.7 2484.62    73.8 2479.65      86 2473.74      93 2470.69
   115.8 2460.05   117.9 2459.34   121.1 2458.48   128.6 2458.16   137.1 2458.76
   142.8  2458.9   158.3 2458.63     167 2458.78   169.9 2458.19   175.5 2457.59
   186.4  2458.3   195.8  2458.8   213.9 2458.28   218.2 2459.02   222.4 2461.46
     230 2467.99   243.7 2478.65   256.5 2487.93   273.6 2499.61   275.9 2500.86
#Mann= 3 ,-1,0
       0      .1       0   169.9    .045       0   186.4      .1       0
Bank Sta=169.9,186.4
XS Rating Curve= 0 ,0
Exp/Cntr(USF)=0,0
Exp/Cntr=0.3,0.1

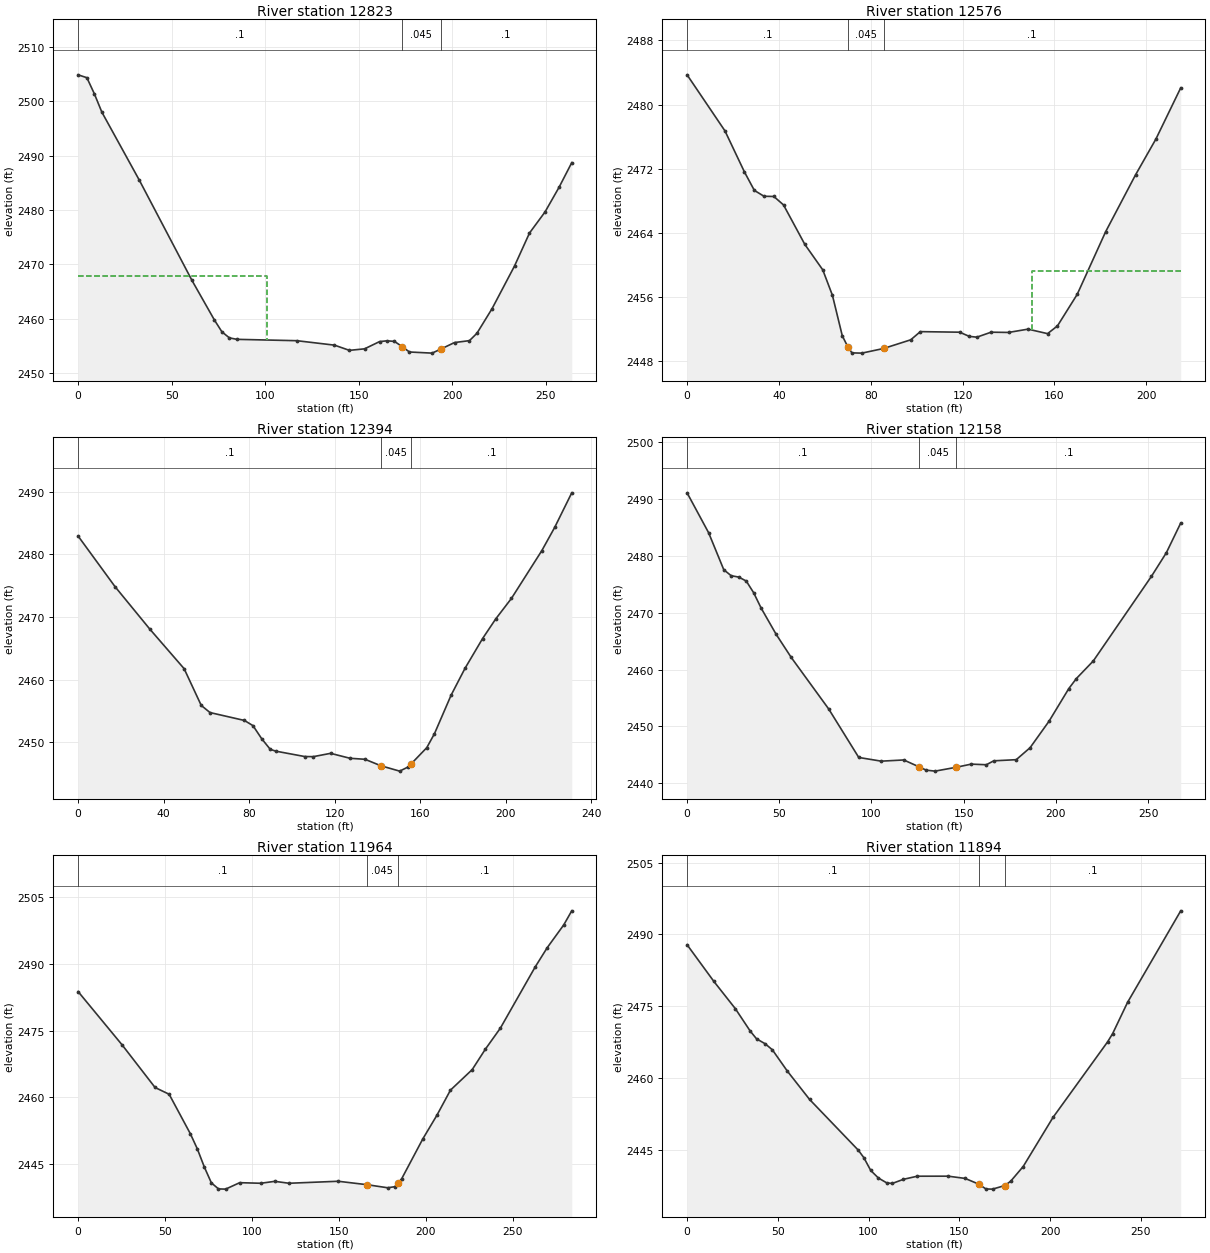
Type RM Length L Ch R = 1 ,12823   ,247.8,247.4,242.3
XS GIS Cut Line= 2
2243404.86820571465637.5846724722243141.63764329 465658.00773335
#Sta/Elev= 30
       0 2504.91     4.7 2504.38     8.7 2501.41    12.7 2498.04    32.8 2485.47
    60.9 2467.04    72.9 2459.75    76.9 2457.58    80.9 2456.46    84.9 2456.19
     117 2455.94   137.1 2455.12   145.1 2454.16   153.2 2454.44   161.2 2455.77
   165.2 2455.92   169.2 2455.81   173.2 2454.87   177.2 2453.86   189.3 2453.65
   193.9 2454.38   201.3  2455.6   209.3 2455.95   213.3 2457.31   221.4 2461.85
   233.4  2469.7   241.4 2475.77   249.7 2479.65   257.2 2484.19     264 2488.73
#Mann= 3 ,-1,0
       0      .1       0   173.2    .045       0   193.9      .1       0
#XS Ineff= 2 , 0
             101 2467.77
Permanent Ineff=
       F       F
Bank Sta=173.2,193.9
XS Rating Curve= 0 ,0
Exp/Cntr(USF)=0,0
Exp/Cntr=0.3,0.1

Type RM Length L Ch R = 1 ,12576   ,178,181.3,183.3
XS GIS Cut Line= 2
2243335.65672163465386.8348694742243133.69534184465460.584811532
#Sta/Elev= 30
       0 2483.71    16.5 2476.72      25 2471.59    29.3  2469.3    33.5 2468.57
    37.8 2468.54      42 2467.49    51.3 2462.56    59.1 2459.39    63.3 2456.22
    67.6 2451.17      70  2449.8    71.8 2449.04    76.1 2449.01    85.6 2449.59
    97.4 2450.67   101.6 2451.69   118.7 2451.62   122.9  2451.1   126.2    2451
   132.4 2451.62     140 2451.59   148.5    2452     157 2451.44   161.3  2452.4
   169.9 2456.33   182.3 2464.15   195.3 2471.23   204.2 2475.71     215 2482.09
#Mann= 3 ,-1,0
       0      .1       0      70    .045       0    85.6      .1       0
#XS Ineff= 2 , 0
                          150.15         2459.26
Permanent Ineff=
       F       F
Bank Sta=70,85.6
XS Rating Curve= 0 ,0
Exp/Cntr(USF)=0,0
Exp/Cntr=0.3,0.1

Type RM Length L Ch R = 1 ,12394   ,238.3,236.5,235.4
XS GIS Cut Line= 2
2243333.38749264465232.5272983982243104.19536501465260.892660728
#Sta/Elev= 30
       0 2482.92    17.3 2474.83    33.5 2468.08    49.6 2461.74    57.6 2455.88
    61.7 2454.74    77.8 2453.48    81.8 2452.65    85.9 2450.55    89.9 2448.86
    92.6 2448.57     106 2447.72     110  2447.7   118.1 2448.23   127.2 2447.44
   134.2 2447.28   141.6 2446.25   150.4 2445.39   154.4 2446.06   155.9 2446.59
   163.1 2449.14   166.7 2451.38   174.5 2457.54     181 2461.82   189.2 2466.56
   195.3 2469.67   202.7 2472.97   216.9 2480.59   222.9 2484.29   230.9 2489.82
#Mann= 3 ,-1,0
       0      .1       0   141.6    .045       0   155.9      .1       0
Bank Sta=141.6,155.9
XS Rating Curve= 0 ,0
Exp/Cntr(USF)=0,0
Exp/Cntr=0.3,0.1

Type RM Length L Ch R = 1 ,12158   ,192.6,193.7,192.8
XS GIS Cut Line= 2
2243327.71442018464991.9890258392243064.48385775465040.777449047
#Sta/Elev= 30
       0 2491.02    11.7    2484    19.9 2477.52    23.9 2476.47      28 2476.23
    32.1 2475.53    36.1 2473.48    40.2 2470.76    48.3 2466.18    56.5 2462.11
    76.8 2453.07    93.1 2444.56   105.3 2443.91   117.5 2444.12   125.6 2442.94
   129.7 2442.33   134.5 2442.16     146 2442.84   154.1 2443.39   162.3 2443.28
   166.3 2443.97   178.5 2444.17     186 2446.27   196.3 2450.93     207 2456.65
   211.1 2458.41   220.3 2461.51   251.8 2476.35   259.9  2480.5   267.7 2485.72
#Mann= 3 ,-1,0
       0      .1       0   125.6    .045       0     146      .1       0
Bank Sta=125.6,146
XS Rating Curve= 0 ,0
Exp/Cntr(USF)=0,0
Exp/Cntr=0.3,0.1

Type RM Length L Ch R = 1 ,11964   ,64.8,69.7,75.8
XS GIS Cut Line= 2
2243303.88751582464826.335309831  2243023.637736464872.854504052
#Sta/Elev= 30
       0 2483.81    25.4 2471.78    44.3 2462.23    52.4 2460.71    64.6 2451.83
    68.6 2448.44    72.7 2444.29    76.7 2440.78    80.8 2439.42    84.9 2439.37
      93 2440.82   105.1 2440.69   113.2 2441.12   121.4 2440.69   149.7 2441.14
   166.4 2440.36   178.1 2439.68   182.2 2439.91  183.872440.652   186.2 2441.69
   198.4 2450.68   206.5 2455.99   214.3 2461.64   226.8 2466.25   234.4 2470.86
     243 2475.57     263 2489.31     270 2493.69   279.5 2498.81   284.1 2501.97
#Mann= 3 ,-1,0
       0      .1       0   166.4    .045       0  183.87      .1       0
Bank Sta=166.4,183.87
XS Rating Curve= 0 ,0
Exp/Cntr(USF)=0,0
Exp/Cntr=0.3,0.1

Type RM Length L Ch R = 1 ,11894   ,109.5,109.3,109.1
XS GIS Cut Line= 4
2243310.21032715464749.8461797592243234.51848319464765.737285122
2243163.42669604464792.0830650672243047.58890168464765.319098139
#Sta/Elev= 30
       0 2487.83    14.7 2480.19    26.6 2474.46    34.8 2469.77    38.3 2468.15
      43 2467.13      47 2465.86    55.2 2461.43    67.5 2455.48    94.3 2444.89
    97.4 2443.31   101.2 2440.63   105.4 2439.06   109.9 2438.06     113 2437.91
   119.2 2438.78   126.8 2439.43   143.8 2439.44   153.2 2438.97   160.6 2437.79
   164.7 2436.76   168.3 2436.73     175 2437.47   178.3 2438.38   185.2 2441.46
   201.6 2451.71   231.7 2467.52   234.5 2469.26   242.7 2475.78     272 2494.92
#Mann= 3 ,-1,0
       0      .1       0   160.6    .045       0     175      .1       0
Bank Sta=160.6,175
XS Rating Curve= 0 ,0
Exp/Cntr(USF)=0,0
Exp/Cntr=0.3,0.1

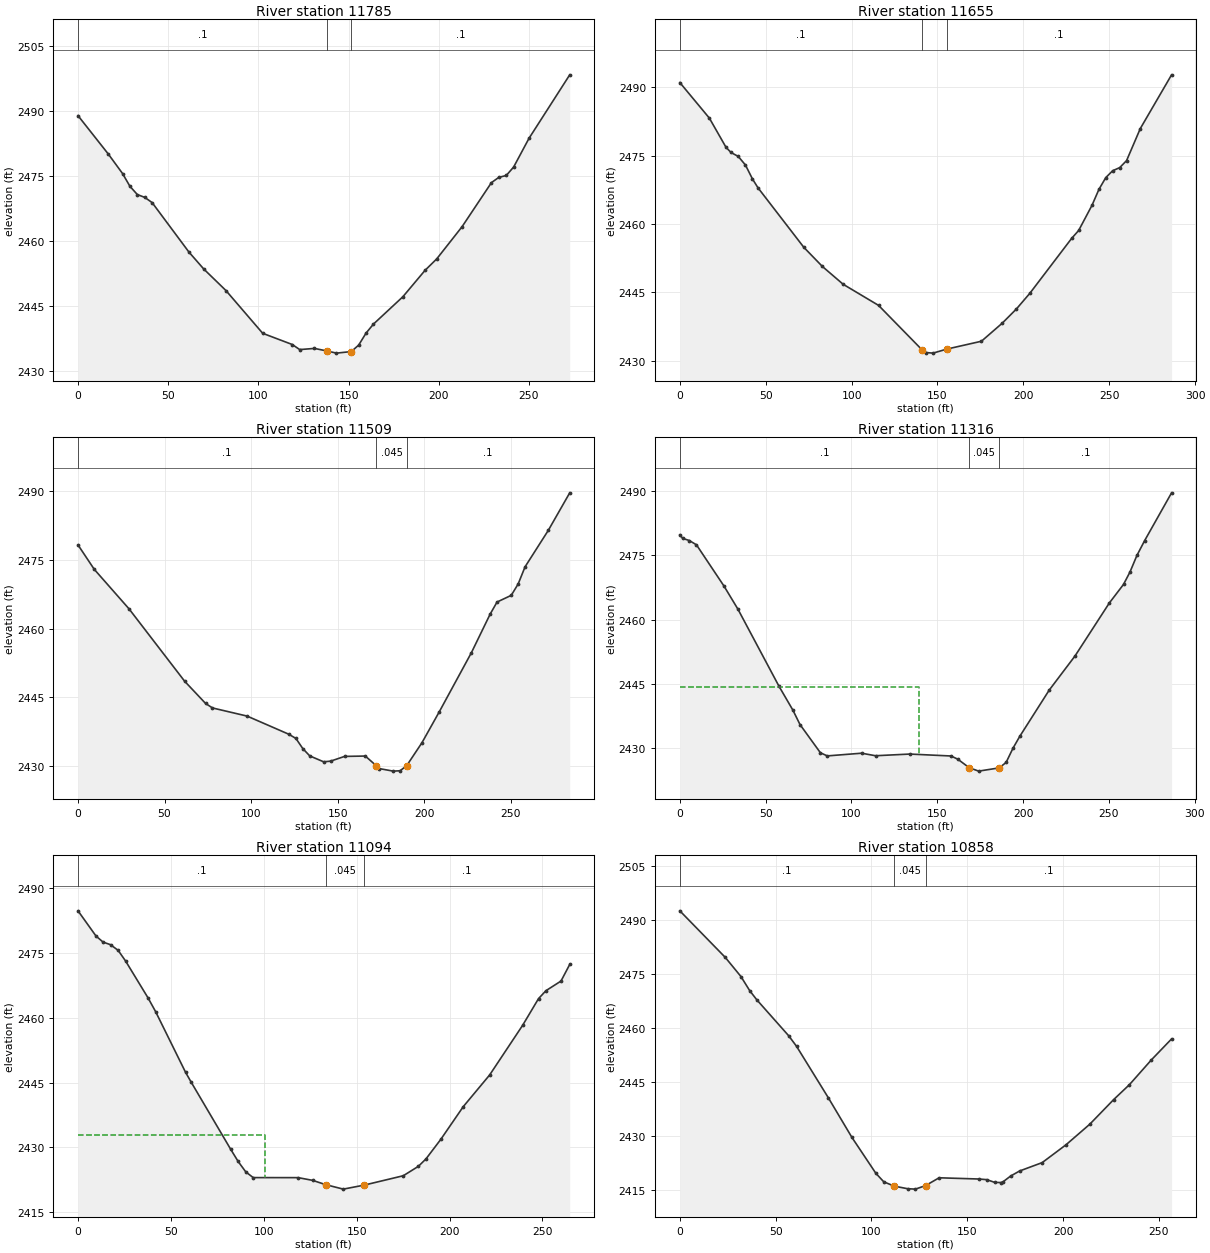
Type RM Length L Ch R = 1 ,11785   ,134,130.4,126.2
XS GIS Cut Line= 2
2243316.36827524 464712.873860512243049.73386934 464656.14313585
#Sta/Elev= 30
       0 2488.99    16.8 2480.11    24.7  2475.6    28.8 2472.64    32.9 2470.74
      37 2470.09    41.1 2468.88    61.5 2457.44    69.7 2453.53      82 2448.55
   102.4 2438.65   118.8 2436.06   122.9 2434.89   131.1 2435.16   138.2 2434.55
   143.3 2434.07   151.5 2434.43   155.6 2435.93   159.7 2438.71   163.8 2440.79
   180.1 2447.11   192.4 2453.22   198.9 2455.88   212.9  2463.3   229.2  2473.5
   233.3 2474.72   237.4 2475.15   241.5  2477.1     250 2483.73   272.6 2498.43
#Mann= 3 ,-1,0
       0      .1       0   138.2    .045       0   151.5      .1       0
Bank Sta=138.2,151.5
XS Rating Curve= 0 ,0
Exp/Cntr(USF)=0,0
Exp/Cntr=0.3,0.1

Type RM Length L Ch R = 1 ,11655   ,144.1,145.2,145.2
XS GIS Cut Line= 3
2243344.84709902 464561.777248452243290.77137228464546.210337604
2243062.10116732464571.330702483
#Sta/Elev= 30
       0 2491.08    17.2 2483.27    26.9 2476.86    29.8 2475.73      34 2474.87
    38.2 2472.98    42.3 2469.91    45.5 2467.98    72.2 2454.91      83 2450.71
    95.1  2446.8   115.7 2442.17   141.1 2432.38   143.4 2431.82   147.4 2431.69
   155.5 2432.58   175.6  2434.3   187.7 2438.26     196  2441.4   203.8 2444.83
   228.1 2456.87   232.2 2458.61     240 2464.16     244 2467.63     248 2470.22
     252 2471.73   256.1 2472.41   260.1 2473.95   268.1 2480.99   286.3 2492.78
#Mann= 3 ,-1,0
       0      .1       0   141.1    .045       0   155.5      .1       0
Bank Sta=141.1,155.5
XS Rating Curve= 0 ,0
Exp/Cntr(USF)=0,0
Exp/Cntr=0.3,0.1

Type RM Length L Ch R = 1 ,11509   ,192.8,193.2,193.4
XS GIS Cut Line= 2
 2243349.5897876464401.0023747632243066.52616384 464424.89735599
#Sta/Elev= 30
       0  2478.3     9.4 2472.96    29.5 2464.31    61.6 2448.49    73.7 2443.63
    77.7 2442.64    97.7 2440.86   121.8 2436.89   125.9 2435.97   129.9 2433.74
   133.9 2432.15   141.9 2430.86   145.9    2431     154 2432.04     166 2432.12
   172.3 2430.01     174 2429.38   182.1 2428.82   186.1  2428.9   189.9 2430.02
   198.7 2435.02   208.8 2441.85   227.3 2454.74   238.1 2463.15   242.1 2465.81
   250.3 2467.27   254.3 2469.76   258.3 2473.52   271.7 2481.48   284.1  2489.7
#Mann= 3 ,-1,0
       0      .1       0   172.3    .045       0   189.9      .1       0
Bank Sta=172.3,189.9
XS Rating Curve= 0 ,0
Exp/Cntr(USF)=0,0
Exp/Cntr=0.3,0.1

Type RM Length L Ch R = 1 ,11316   ,223.8,222.8,221.8
XS GIS Cut Line= 2
 2243333.8974562464212.5877903712243047.97460392464230.741622262
#Sta/Elev= 30
       0  2479.8     1.7 2478.97     5.5 2478.48     9.7 2477.47    25.8 2467.81
    33.8  2462.5    57.8 2444.47    65.9  2438.9      70 2435.57    81.9 2428.98
    85.9 2428.25   105.9 2428.88     114 2428.29     134 2428.68     158 2428.23
     162 2427.47  168.562425.505   174.1  2424.7   186.1 2425.46   190.1 2426.73
   194.1 2430.04   198.1 2432.84   215.2 2443.59   230.2 2451.53   250.2 2463.89
   258.5 2468.24   262.3 2471.16   266.3 2474.99   270.8 2478.45   286.5  2489.6
#Mann= 3 ,-1,0
       0      .1       0  168.56    .045       0   186.1      .1       0
#XS Ineff= 2 , 0
          139.54 2444.33
Permanent Ineff=
       F       F
Bank Sta=168.56,186.1
XS Rating Curve= 0 ,0
Exp/Cntr(USF)=0,0
Exp/Cntr=0.3,0.1

Type RM Length L Ch R = 1 ,11094   ,236.3,235.2,233.6
XS GIS Cut Line= 2
2243269.50425006463983.4783764572243007.56238557464021.298859564
#Sta/Elev= 30
       0 2484.78     9.7 2478.94    13.5 2477.54    17.5 2476.94    21.6 2475.63
    25.6 2473.17    37.7 2464.62    41.8 2461.42    57.9 2447.39      61 2445.05
    82.2 2429.56    86.2 2426.75    90.3 2424.34    94.3 2423.01   118.5    2423
   126.3 2422.37   133.3 2421.38   142.8 2420.34  154.212421.284   175.1 2423.44
   183.2 2425.61   187.3 2427.33   195.3 2431.87   207.4 2439.45   221.6 2446.78
   239.3 2458.24   247.9 2464.45   251.9 2466.29     260 2468.52   264.7 2472.37
#Mann= 3 ,-1,0
       0      .1       0   133.3    .045       0  154.21      .1       0
#XS Ineff= 2 , 0
           100.4 2432.78
Permanent Ineff=
       F       F
Bank Sta=133.3,154.21
XS Rating Curve= 0 ,0
Exp/Cntr(USF)=0,0
Exp/Cntr=0.3,0.1

Type RM Length L Ch R = 1 ,10858   ,253.7,252.6,251.8
XS GIS Cut Line= 2
2243219.06349196463743.487100144 2242970.9233023463808.738779649
#Sta/Elev= 30
       0 2492.49    23.7 2479.56    31.9 2474.23    36.5 2470.28    40.2 2467.75
    56.8 2457.79    60.9 2454.86    77.4 2440.64    89.8 2429.55   102.3 2419.58
   106.4 2417.23   111.8 2416.03   118.8 2415.31   122.9 2415.19   128.2 2416.16
   135.3 2418.34     156    2418   160.2 2417.82   164.3 2417.06   167.5 2417.02
   168.4 2417.12   172.6 2418.82   177.3 2420.23   189.1 2422.56   201.5  2427.5
   213.9 2433.21   226.4 2440.07   234.6  2444.2   246.1 2451.11   256.6 2456.91
#Mann= 3 ,-1,0
       0      .1       0   111.8    .045       0   128.2      .1       0
Bank Sta=111.8,128.2
XS Rating Curve= 0 ,0
Exp/Cntr(USF)=0,0
Exp/Cntr=0.3,0.1

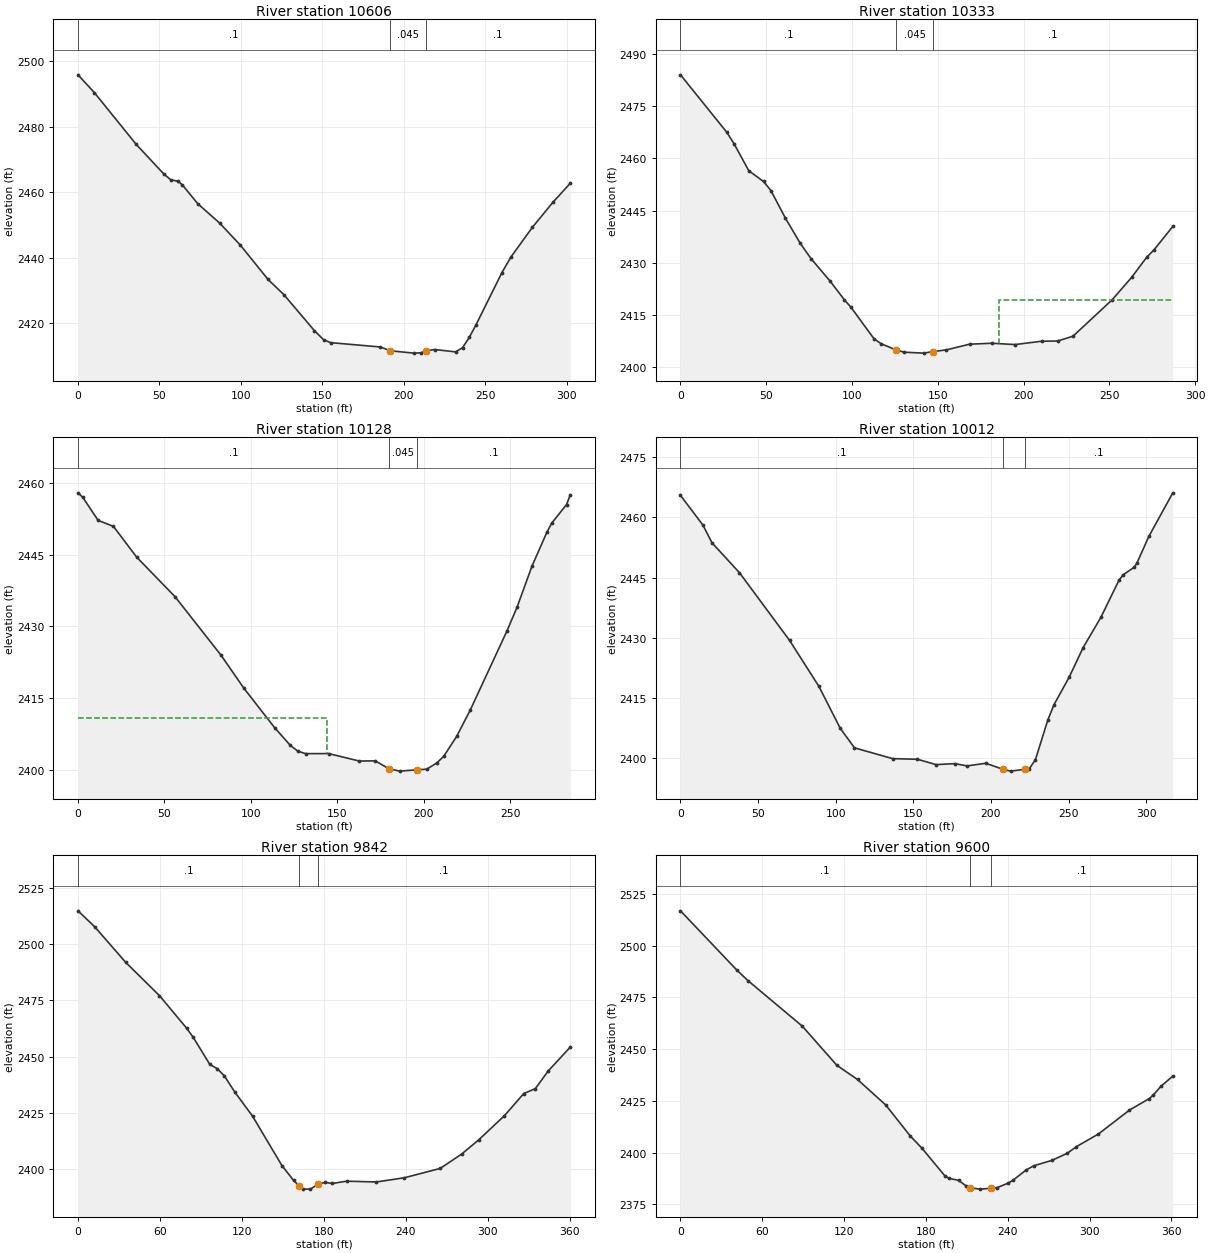
Type RM Length L Ch R = 1 ,10606   ,275.2,272.8,274.8
XS GIS Cut Line= 2
2243185.67092449463480.3110112832242902.01730119463584.947681212
#Sta/Elev= 30
       0 2495.83    10.1 2490.36    35.7 2474.62    52.8  2465.5      57 2463.78
    61.3 2463.38    64.1 2462.23    73.5 2456.51    86.9 2450.61    99.7 2443.84
   116.7 2433.37   126.4 2428.74   145.1 2417.78   150.8 2414.98   155.1 2414.09
   185.6 2412.77   191.8 2411.61   206.2 2410.89   210.5 2410.97   213.6 2411.55
     219 2411.99   231.8 2411.27   236.1 2412.54   240.3 2415.75   244.3 2419.45
   260.3 2435.47   265.9 2440.28     279 2449.29   291.5 2456.87   302.3 2462.76
#Mann= 3 ,-1,0
       0      .1       0   191.8    .045       0   213.6      .1       0
Bank Sta=191.8,213.6
XS Rating Curve= 0 ,0
Exp/Cntr(USF)=0,0
Exp/Cntr=0.3,0.1

Type RM Length L Ch R = 1 ,10333   ,218.9,204.6,198.8
XS GIS Cut Line= 2
2243101.20517889463229.435140008 2242833.9404316463334.071809937
#Sta/Elev= 30
       0 2483.93    26.9 2467.51    31.2 2464.18    39.8 2456.43    48.4 2453.34
    52.7 2450.75    61.2 2442.79    69.8 2435.62    76.1  2431.2    87.1 2424.84
    95.6 2419.36    99.4 2417.25   112.8 2408.23   117.1 2406.76   125.7 2405.04
   130.3 2404.38   141.9 2404.11   147.2 2404.57   154.9 2405.03   168.6 2406.68
   181.5 2406.94   195.1 2406.57   210.5 2407.52   219.8 2407.58   228.8 2408.96
   251.7 2419.44     263 2425.84   271.7 2431.56     276 2433.71     287 2440.44
#Mann= 3 ,-1,0
       0      .1       0   125.7    .045       0   147.2      .1       0
#XS Ineff= 2 , 0
                          185.56         2419.33
Permanent Ineff=
       F       F
Bank Sta=125.7,147.2
XS Rating Curve= 0 ,0
Exp/Cntr(USF)=0,0
Exp/Cntr=0.3,0.1

Type RM Length L Ch R = 1 ,10128   ,104.9,115.9,129.7
XS GIS Cut Line= 4
2242970.65806203463089.1300345282242818.64221764463162.556555591
2242771.02970789463239.4249448292242750.37849884 463254.33970692
#Sta/Elev= 30
       0 2457.91     2.8 2456.94    11.6 2452.15    20.5 2450.88    33.9 2444.45
    56.1 2436.17    82.7 2423.92      96 2416.97   113.8 2408.71   122.7 2405.08
   127.1 2403.84   131.6 2403.32   144.9 2403.33   162.7 2401.77   171.9 2401.81
  179.612400.189     186 2399.66   195.8 2399.93   201.6 2400.06   207.4 2401.35
   211.5 2402.77     219 2406.96   226.7 2412.35   248.1 2429.04   253.9 2433.98
   262.5 2442.55   271.1 2449.63     274  2451.6   282.5 2455.45   284.7 2457.52
#Mann= 3 ,-1,0
       0      .1       0  179.61    .045       0   195.8      .1       0
#XS Ineff= 2 , 0
          143.73 2410.85
Permanent Ineff=
       F       F
Bank Sta=179.61,195.8
XS Rating Curve= 0 ,0
Exp/Cntr(USF)=0,0
Exp/Cntr=0.3,0.1

Type RM Length L Ch R = 1 ,10012   ,179.8,170.9,163.1
XS GIS Cut Line= 4
2242945.88770018463035.2033112252242843.88258426463092.571902703
2242719.40168527463091.9982580072242655.12355377 463131.96228634
#Sta/Elev= 30
       0  2465.5    14.5 2458.08    20.3 2453.69      38 2446.25    70.3 2429.38
    89.2 2417.93   102.9 2407.52   112.1 2402.64   136.7 2399.95   152.7 2399.79
   164.7 2398.46   176.7 2398.71   184.7 2398.14   196.7  2398.8   207.7  2397.3
   212.7 2396.84   221.8 2397.29   224.7 2397.41   228.7 2399.71   236.7  2409.6
   240.7 2413.42   250.5 2420.29   259.4 2427.58   270.9 2435.16   282.5 2444.36
   285.2 2445.72   292.4 2447.63   294.1 2448.67   301.8 2455.31   317.2 2466.14
#Mann= 3 ,-1,0
       0      .1       0   207.7    .045       0   221.8      .1       0
Bank Sta=207.7,221.8
XS Rating Curve= 0 ,0
Exp/Cntr(USF)=0,0
Exp/Cntr=0.3,0.1

Type RM Length L Ch R = 1 ,9842    ,241.8,242,241.3
XS GIS Cut Line= 2
2242865.45750085462818.4525569142242591.88933971463052.939552176
#Sta/Elev= 30
       0 2514.94    12.2 2507.83    34.9 2491.98    59.6 2477.16    79.4 2462.71
    84.1 2458.77    96.5 2446.47   101.8 2444.64   107.1 2441.41   114.8 2434.14
   127.7 2423.48   149.2 2401.46   157.8 2394.79   161.7  2392.5     165 2390.97
   170.1 2390.94   175.5 2393.13   180.8 2393.95   186.1 2393.47   196.6 2394.48
   218.4 2394.13   238.8    2396   265.1 2400.17   280.9 2406.63   293.1 2412.82
   312.1 2423.68   326.2 2433.53   334.7 2435.73   344.1 2443.58   360.3 2454.25
#Mann= 3 ,-1,0
       0      .1       0   161.7    .045       0   175.5      .1       0
Bank Sta=161.7,175.5
XS Rating Curve= 0 ,0
Exp/Cntr(USF)=0,0
Exp/Cntr=0.3,0.1

Type RM Length L Ch R = 1 ,9600    ,203.9,206.4,210.1
XS GIS Cut Line= 2
2242695.35063466462654.0966251262242438.17134953462907.493861942
#Sta/Elev= 30
       0 2516.76    41.2 2488.21    49.4 2483.08    89.3 2461.05   114.7  2442.1
   129.8 2435.28   150.5 2422.96   168.5 2407.96     177 2402.11   193.9 2388.71
   196.8 2387.57   203.9 2386.54   209.6 2383.78   212.2 2382.97   219.4 2382.31
   227.9 2382.71   232.4 2383.09   240.3 2385.22   243.8 2386.59   253.3  2391.5
     259 2393.58   272.3  2396.2   283.7 2399.66   290.1 2402.74   306.5 2408.96
   329.2 2420.49   343.8 2426.08   346.7 2427.79   352.3 2431.99     361  2436.9
#Mann= 3 ,-1,0
       0      .1       0   212.2    .045       0   227.9      .1       0
Bank Sta=212.2,227.9
XS Rating Curve= 0 ,0
Exp/Cntr(USF)=0,0
Exp/Cntr=0.3,0.1