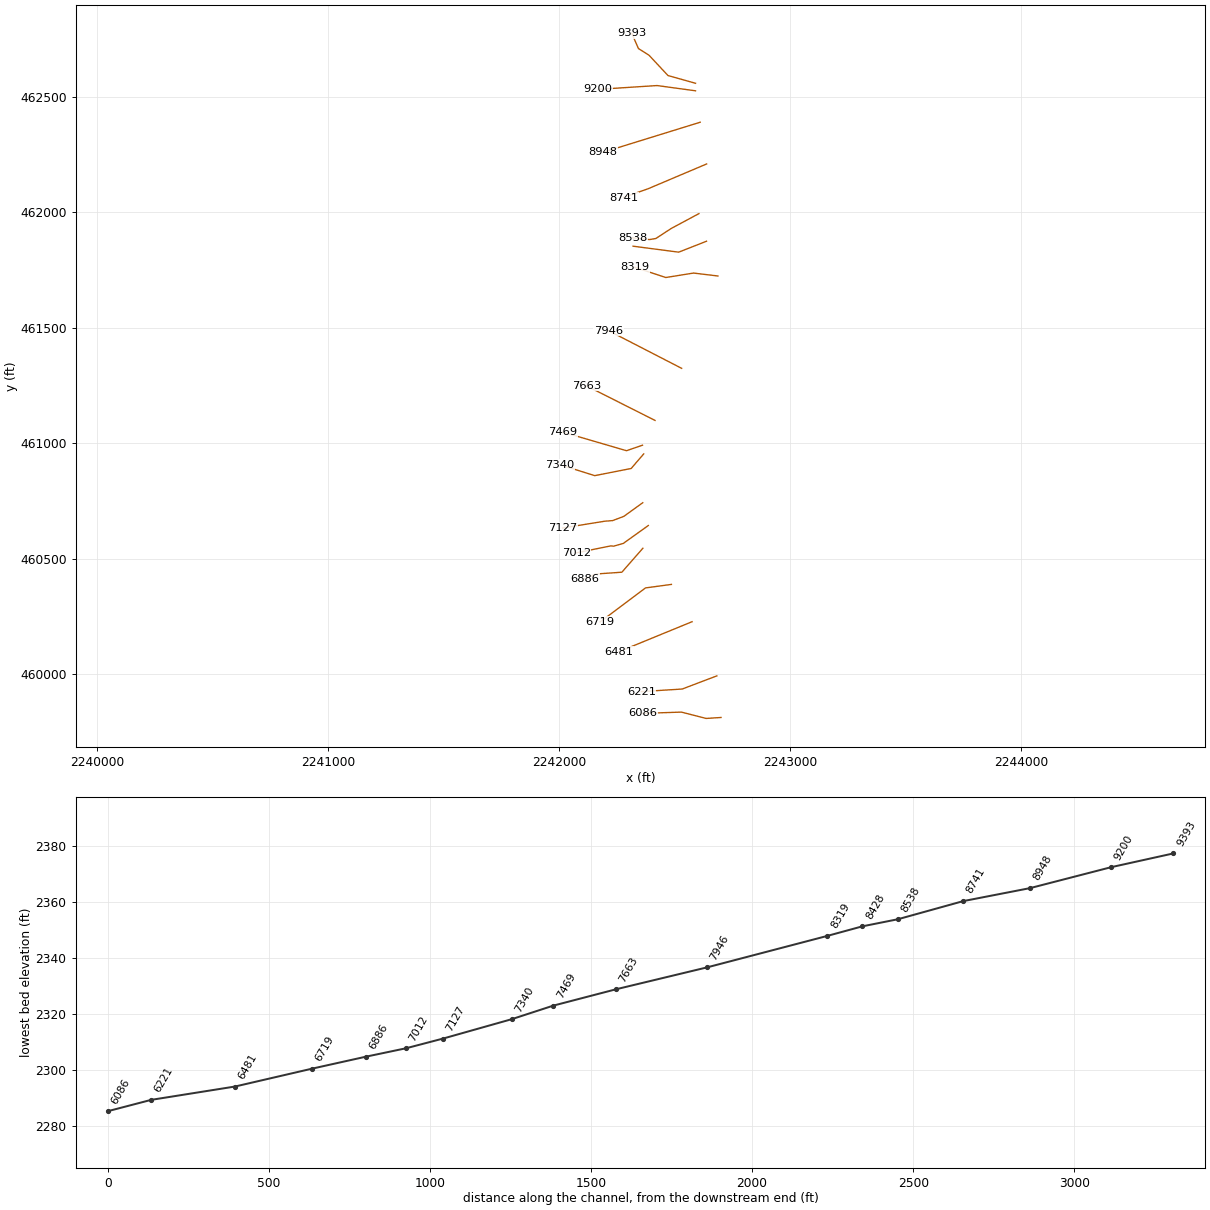
HEC-RAS study LWSLKRN.prj: LWSLKRN

--- LWSLKRN.g01 (geometry) --- (continued)

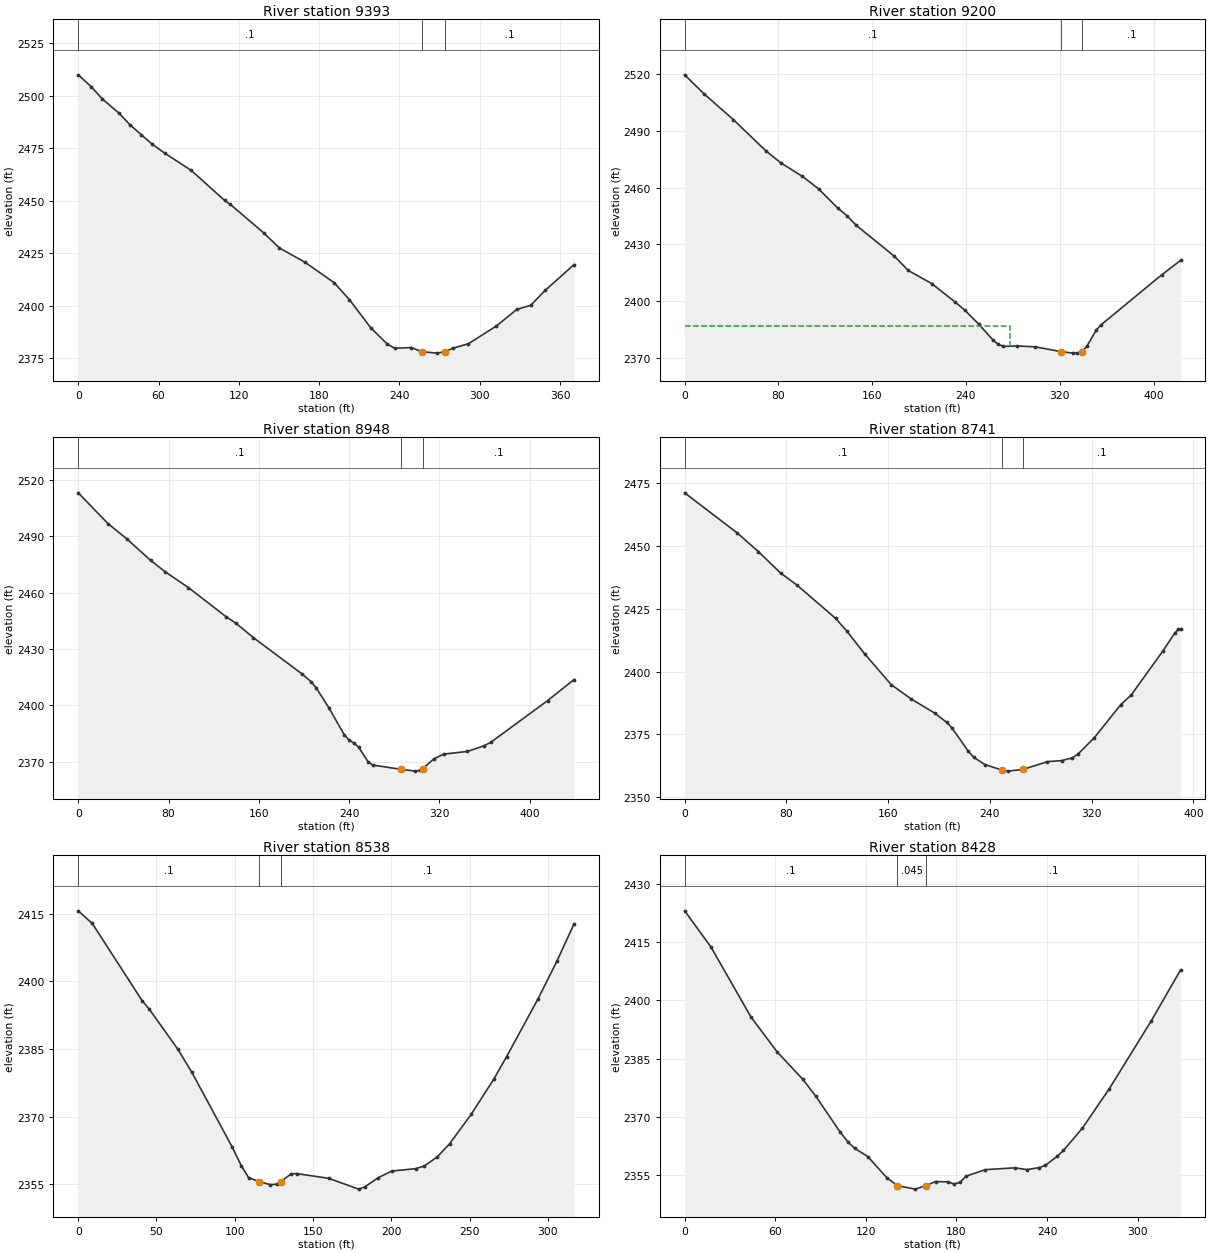
Type RM Length L Ch R = 1 ,9393    ,182.4,193,200.2
XS GIS Cut Line= 5
2242589.48141069462558.5274208892242470.22343033  462591.9951753
2242388.23598097462679.7994132342242342.20276464462708.914438947
2242313.47811338462775.002116027
#Sta/Elev= 30
       0 2509.84     9.7  2504.2      18 2498.38    30.4 2491.65    38.7 2486.06
    47.1 2481.33    55.4 2476.79    64.8 2472.49    84.3 2464.44   109.4 2450.05
   113.6 2448.22   138.6 2434.64   150.3 2427.46   169.3 2420.71   191.2 2410.95
   202.6 2402.89   218.5 2389.55   230.9 2381.71   236.5 2379.76   248.8 2380.08
   256.6 2378.15   267.7 2377.43     274 2378.05   279.8 2379.76   291.4 2381.86
   312.4 2390.33   327.6 2398.21     338 2400.17   348.8 2407.26   370.5 2419.59
#Mann= 3 ,-1,0
       0      .1       0   256.6    .045       0     274      .1       0
Bank Sta=256.6,274
XS Rating Curve= 0 ,0
Exp/Cntr(USF)=0,0
Exp/Cntr=0.3,0.1

Type RM Length L Ch R = 1 ,9200    ,247.5,252,254.2
XS GIS Cut Line= 3
2242589.36797417462525.974154221 2242422.9578485462548.666444085
2242168.29992892462532.277568072
#Sta/Elev= 30
       0 2519.61    16.3 2509.68    41.6 2495.88    69.8 2479.13    81.9 2473.15
   100.5 2465.91   114.2 2459.35   130.4  2449.3   138.5  2445.1   146.5    2440
   178.8 2423.77   190.8  2416.2   210.8 2409.25   230.9 2399.46   238.9 2395.24
   250.9 2387.81   262.9 2379.56   266.9 2377.45   271.8 2376.06   283.1 2376.31
     299 2375.83   320.7 2373.37   331.1 2372.51   335.1 2372.59   339.1 2373.34
   343.1 2376.16   351.1 2384.66   355.1 2387.41   407.2 2414.01   423.1 2421.52
#Mann= 3 ,-1,0
       0      .1       0   320.7    .045       0   339.1      .1       0
#XS Ineff= 2 , 0
          277.41 2386.93
Permanent Ineff=
       F       F
Bank Sta=320.7,339.1
XS Rating Curve= 0 ,0
Exp/Cntr(USF)=0,0
Exp/Cntr=0.3,0.1

Type RM Length L Ch R = 1 ,8948    ,205.9,207.4,208.7
XS GIS Cut Line= 2
 2242609.5388985462389.8204150362242189.73153601462259.970089703
#Sta/Elev= 30
       0  2513.2    26.5 2496.75    42.8 2488.83    64.2 2477.19    76.8 2471.29
    97.7 2462.71   131.2 2447.15   139.6 2443.83   155.1 2436.15   198.2 2416.83
   206.3 2412.67   210.8 2409.43   222.3 2398.51   235.9 2384.18   240.1 2381.43
   244.3 2379.95   248.5 2377.72   256.8    2370     261 2368.25   285.72365.989
   298.7 2365.01   302.9 2365.36   305.4 2366.38     315 2371.51   323.8 2374.06
   344.8  2375.5   359.8 2378.57   365.7 2380.41   415.9 2402.58   439.4  2413.8
#Mann= 3 ,-1,0
       0      .1       0   285.7    .045       0   305.4      .1       0
Bank Sta=285.7,305.4
XS Rating Curve= 0 ,0
Exp/Cntr(USF)=0,0
Exp/Cntr=0.3,0.1

Type RM Length L Ch R = 1 ,8741    ,200.9,203,203.5
XS GIS Cut Line= 4
2242637.60535245462209.2803946432242384.67621691462102.155169404
2242277.67485439462064.638958927 2242278.1231834462062.728163666
#Sta/Elev= 30
       0 2471.27    41.3 2455.29      58 2447.84    75.4 2439.32    88.4 2434.47
   118.8 2421.19   127.5 2416.18   141.5 2407.12   162.3 2394.88   178.2  2389.1
   196.5 2383.51     206 2379.81   210.1 2377.66   223.1 2368.25   227.4 2365.84
   236.1 2362.97   249.2 2360.84   254.4 2360.36   266.2 2361.06   285.3 2364.15
   296.4 2364.55   304.9 2365.65   309.1 2367.06   321.8 2373.49     343 2386.88
   351.2 2390.74   376.3 2408.42   385.4 2415.37   388.1 2416.81     390 2417.05
#Mann= 3 ,-1,0
       0      .1       0   249.2    .045       0   266.2      .1       0
Bank Sta=249.2,266.2
XS Rating Curve= 0 ,0
Exp/Cntr(USF)=0,0
Exp/Cntr=0.3,0.1

Type RM Length L Ch R = 1 ,8538    ,117.9,109.8,102.9
XS GIS Cut Line= 5
 2242604.1358287461994.248697281 2242484.6989537461930.301512267
2242417.66736297461886.5852574422242390.25399998461881.932933433
 2242317.1343993461889.497030055
#Sta/Elev= 30
       0  2415.7       9 2412.89    40.8 2395.75    45.3 2393.89    63.5 2385.03
    72.6 2379.82    98.3 2363.26   104.3 2358.99   108.8 2356.44115.79042355.508
   122.5 2354.88     127 2354.96   129.4 2355.56   136.1 2357.27   139.6 2357.32
     160 2356.27   179.1 2353.87   182.9 2354.34   191.6  2356.4   200.3 2357.88
   215.5 2358.42   221.1 2359.01   229.2 2360.99   237.3 2363.97     251 2370.48
   265.5 2378.32   273.6 2383.28   293.7 2396.13   305.7 2404.45   316.8 2412.86
#Mann= 3 ,-1,0
       0      .1       0115.7904    .045       0   129.4      .1       0
Bank Sta=115.7904,129.4
XS Rating Curve= 0 ,0
Exp/Cntr(USF)=0,0
Exp/Cntr=0.3,0.1

Type RM Length L Ch R = 1 ,8428    ,104,109,112.5
XS GIS Cut Line= 3
2242637.04620388461874.8316416052242516.51167411461827.457373688
2242319.21883684461853.243367617
#Sta/Elev= 30
       0 2423.09    17.4 2413.77    43.9 2395.72    61.1 2386.79    78.3 2379.63
    86.9 2375.27   102.9  2366.1   108.4 2363.38   112.7 2361.84   121.3 2359.74
   133.9 2354.29   140.92352.239   152.8 2351.34   159.9 2352.27   166.2 2353.29
   174.2 2353.22   178.3 2352.69   182.3 2353.05   186.3 2354.66   199.1 2356.36
   218.6 2356.83   226.7 2356.38   234.6 2356.86   238.8 2357.45   246.8 2359.81
   250.9 2361.31   263.4 2367.04   281.2 2377.19   308.9 2394.62   328.5 2407.87
#Mann= 3 ,-1,0
       0      .1       0   140.9    .045       0   159.9      .1       0
Bank Sta=140.9,159.9
XS Rating Curve= 0 ,0
Exp/Cntr(USF)=0,0
Exp/Cntr=0.3,0.1

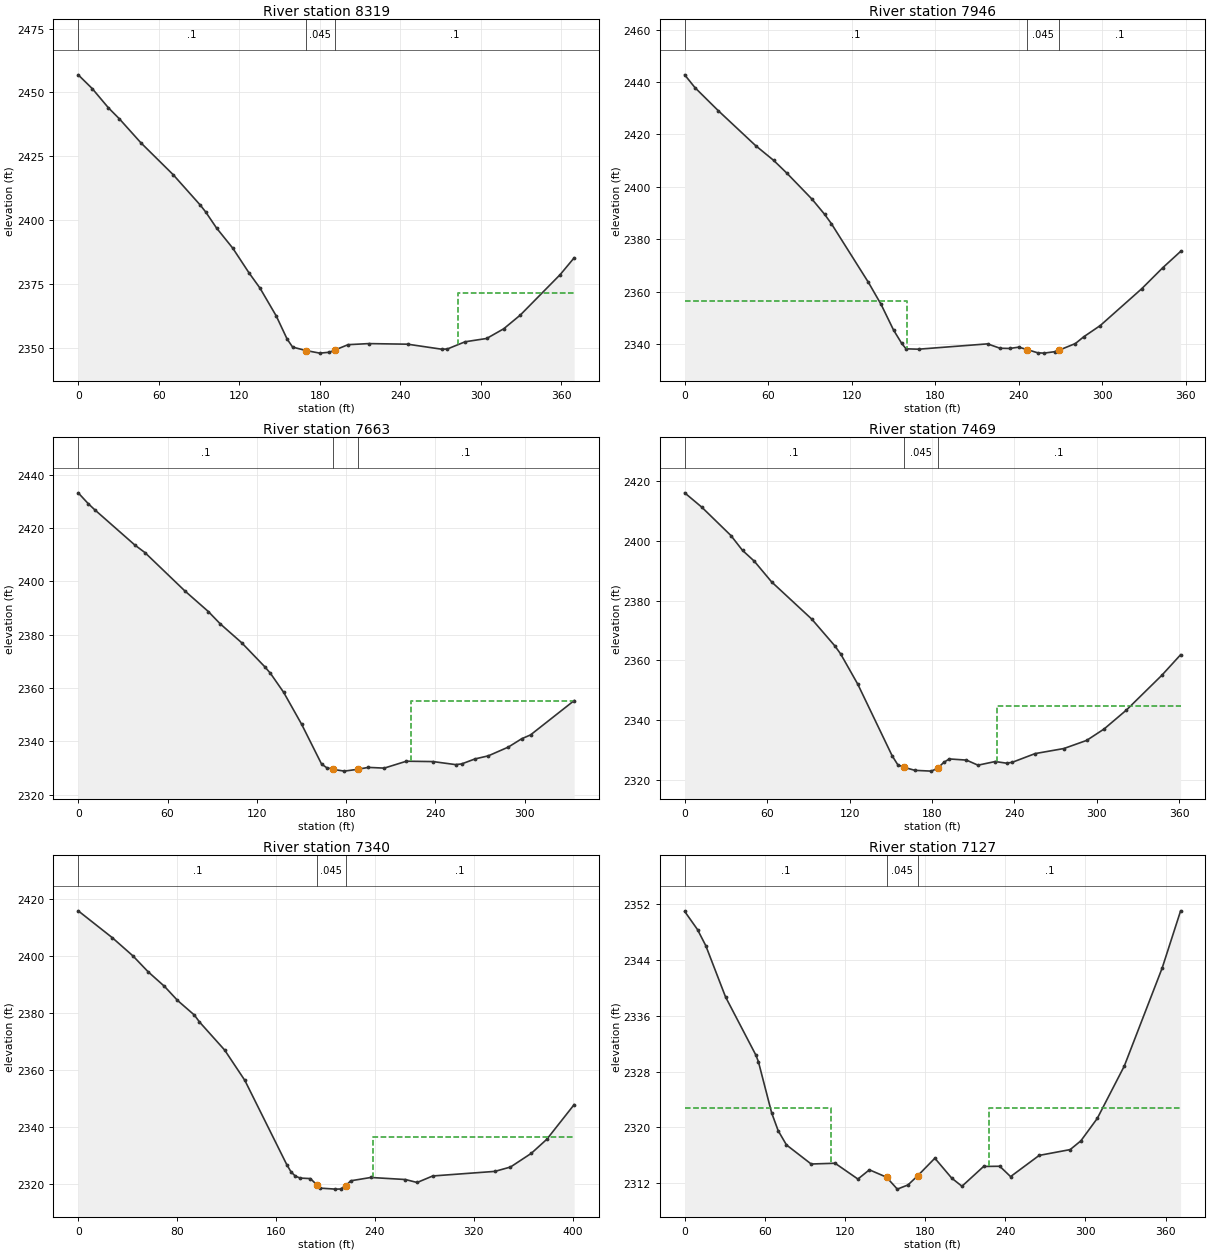
Type RM Length L Ch R = 1 ,8319    ,384.6,373.6,365.9
XS GIS Cut Line= 4
2242686.51445098461724.3475871552242580.61709828461736.954414857
2242460.74196631461717.7169809182242326.25218189 461761.97706245
#Sta/Elev= 30
       0 2456.89    10.4 2451.53    22.5 2443.98    30.6  2439.7    46.7 2430.28
    70.8 2417.77      91 2405.86      95 2403.19   103.1  2396.9   115.2    2389
   127.3 2379.33   135.5 2373.35   147.6 2362.45   155.7 2353.41   159.8 2350.27
   169.7 2348.93     180 2347.91   187.1 2348.25  191.032349.063   201.1 2351.22
   216.5 2351.64   245.5 2351.41   270.8 2349.45     275 2349.51   288.3 2352.35
   304.4 2353.65   317.1 2357.44   329.5 2362.83   359.2 2378.67   369.6 2385.23
#Mann= 3 ,-1,0
       0      .1       0   169.7    .045       0  191.03      .1       0
#XS Ineff= 2 , 0
                          283.06         2371.61
Permanent Ineff=
       F       F
Bank Sta=169.7,191.03
XS Rating Curve= 0 ,0
Exp/Cntr(USF)=0,0
Exp/Cntr=0.3,0.1

Type RM Length L Ch R = 1 ,7946    ,279.2,282.3,282.5
XS GIS Cut Line= 2
2242529.48713657461324.4777812292242212.85911809 461487.58918469
#Sta/Elev= 30
       0 2442.73     7.4 2437.84      24 2429.13      51 2415.72    63.9 2410.12
    73.5 2405.19    91.5 2395.31   100.5 2389.56   105.4 2385.97     132 2363.58
   141.1 2355.18     150 2345.46   155.9 2340.33     159 2338.28     168 2338.14
   217.5 2340.17   226.5  2338.5   233.4 2338.42     240 2338.92   246.1 2337.98
   253.5 2336.77     258 2336.64   265.8 2337.19   269.12337.807   280.6 2340.29
   286.6 2342.86   298.5 2347.16   328.2 2361.16   343.4 2369.21   356.2 2375.42
#Mann= 3 ,-1,0
       0      .1       0   246.1    .045       0   269.1      .1       0
#XS Ineff= 2 , 0
          159.47 2356.54
Permanent Ineff=
       F       F
Bank Sta=246.1,269.1
XS Rating Curve= 0 ,0
Exp/Cntr(USF)=0,0
Exp/Cntr=0.3,0.1

Type RM Length L Ch R = 1 ,7663    ,192.4,194.6,197
XS GIS Cut Line= 2
2242414.20697261461099.0489331212242116.68583884461249.070182779
#Sta/Elev= 30
       0 2433.21     6.8 2429.11    11.2 2426.81    38.1  2413.6    44.8 2410.81
    71.6 2396.44    87.4 2388.69    95.4 2384.07   109.8 2376.99   125.2 2368.05
   129.1 2365.54     138 2358.39   150.1 2346.39   163.5 2331.46   166.9 2330.12
   171.5 2329.44   178.8 2328.81   187.7 2329.49   194.9 2330.21   205.6 2329.94
   220.5 2332.53   238.4 2332.39   253.5 2331.26   257.6 2331.51   266.6 2333.39
   275.5 2334.54     289 2337.84   297.9 2340.94   303.9  2342.4   333.2 2355.27
#Mann= 3 ,-1,0
       0      .1       0   171.5    .045       0   187.7      .1       0
#XS Ineff= 2 , 0
                          223.26         2355.12
Permanent Ineff=
       F       F
Bank Sta=171.5,187.7
XS Rating Curve= 0 ,0
Exp/Cntr(USF)=0,0
Exp/Cntr=0.3,0.1

Type RM Length L Ch R = 1 ,7469    ,121.8,129,138.1
XS GIS Cut Line= 3
2242359.99761349460991.8908976522242290.66006113460967.937925018
2242014.57053445461048.621622312
#Sta/Elev= 30
       0 2416.08    12.5 2411.26    33.7 2401.77    42.1 2396.82    50.6 2393.24
    63.3 2386.27    92.6 2373.78   109.3 2364.87   113.5  2362.2     126 2352.05
     151 2328.11   155.1 2325.11   159.3 2324.29   167.6 2323.22   179.6 2322.96
   184.3 2323.98   188.5 2325.86   192.6 2327.04   205.1 2326.65   213.5 2324.95
     226 2326.17   234.3 2325.62   238.5 2325.92   255.1 2328.83     276 2330.52
   292.6 2333.24   305.3 2337.06   321.5 2343.38   347.3 2355.02     361 2361.91
#Mann= 3 ,-1,0
       0      .1       0   159.3    .045       0   184.3      .1       0
#XS Ineff= 2 , 0
                          227.24         2344.88
Permanent Ineff=
       F       F
Bank Sta=159.3,184.3
XS Rating Curve= 0 ,0
Exp/Cntr(USF)=0,0
Exp/Cntr=0.3,0.1

Type RM Length L Ch R = 1 ,7340    ,210.9,212.6,207.9
XS GIS Cut Line= 4
2242365.04034457460954.0704145452242310.83098545460891.036276034
2242153.15554703460860.0300533592242003.04038687460907.281810574
#Sta/Elev= 30
       0  2415.8    27.6 2406.36    44.3 2399.97    56.5 2394.43    69.8 2389.28
    80.3 2384.37      94  2379.2    98.1 2376.79   118.5 2366.91   134.8 2356.28
   168.7 2326.72   172.1 2324.21   175.6 2322.69   179.6 2321.99   187.8 2321.81
   192.82319.719   195.9 2318.46   208.1 2318.11   212.2 2318.15   216.62319.342
   220.4 2321.03   236.7  2322.2   264.7 2321.48   274.2 2320.44   286.8 2322.73
   337.1 2324.34   349.7 2325.87   366.5 2330.66   379.1 2335.62   401.2 2347.78
#Mann= 3 ,-1,0
       0      .1       0   192.8    .045       0   216.6      .1       0
#XS Ineff= 2 , 0
                          238.55         2336.38
Permanent Ineff=
       F       F
Bank Sta=192.8,216.6
XS Rating Curve= 0 ,0
Exp/Cntr(USF)=0,0
Exp/Cntr=0.3,0.1

Type RM Length L Ch R = 1 ,7127    ,113.9,114.8,114.5
XS GIS Cut Line= 5
2242360.97058932460742.7831261032242279.01117493460683.651995427
2242230.48025429460665.448879617 2242196.4987119460662.783660606
2242014.51757185460633.421500687
#Sta/Elev= 30
       0 2350.89     9.6 2348.29    15.8 2345.99    30.6 2338.66    53.3 2330.35
    55.2 2329.41    65.1  2322.1      70 2319.54    76.2 2317.51    94.7 2314.78
   112.6 2314.89   129.7 2312.63   138.3 2313.95   151.1  2312.9   159.2 2311.19
   167.2 2311.79174.64132313.135   187.3 2315.61   199.9 2312.77   207.6  2311.6
   223.8 2314.43   235.9 2314.46     244 2312.98   265.4 2316.01   288.6 2316.84
   296.6 2318.09   308.9  2321.3   329.1 2328.77   357.5  2342.8   371.3 2350.97
#Mann= 3 ,-1,0
       0      .1       0   151.1    .045       0174.6413      .1       0
#XS Ineff= 2 , 0
          109.56 2322.77  227.89         2322.85
Permanent Ineff=
       F       F
Bank Sta=151.1,174.6413
XS Rating Curve= 0 ,0
Exp/Cntr(USF)=0,0
Exp/Cntr=0.3,0.1

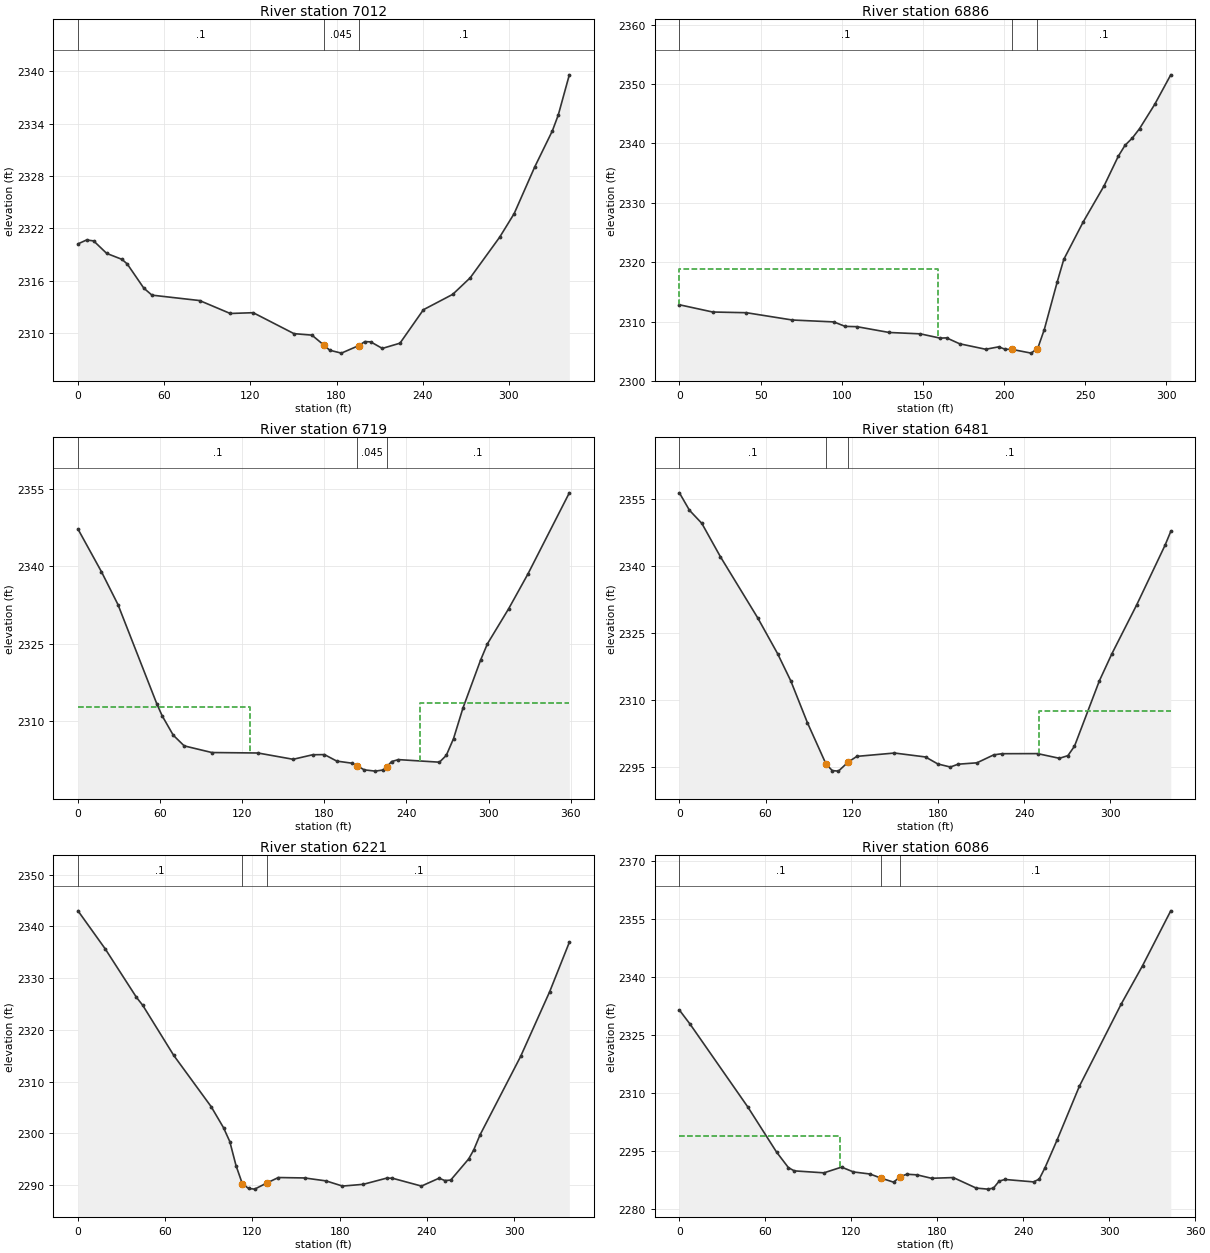
Type RM Length L Ch R = 1 ,7012    ,127.6,126.1,122.2
XS GIS Cut Line= 5
2242385.06295692 460644.12712753 2242276.8472145 460566.73784287
2242234.77208173460554.7247308752242222.81765019460556.018087487
 2242072.5660279 460525.52488155
#Sta/Elev= 30
       0 2320.23       6 2320.68    10.9 2320.57      20 2319.14    30.6 2318.46
    34.3 2317.93    45.8 2315.17    51.5 2314.36    84.7 2313.74     106 2312.26
     122 2312.35   150.4 2309.95   162.9 2309.78   171.2 2308.64   175.3 2308.05
   183.4 2307.72   195.6 2308.59   199.7 2309.04   203.8 2309.01   211.9 2308.26
   224.2 2308.86   240.5 2312.69   260.9 2314.45   273.1 2316.35   293.6    2321
   303.7  2323.7     318 2329.04   330.3 2333.18   334.4 2334.99   342.1 2339.59
#Mann= 3 ,-1,0
       0      .1       0   171.2    .045       0   195.6      .1       0
Bank Sta=171.2,195.6
XS Rating Curve= 0 ,0
Exp/Cntr(USF)=0,0
Exp/Cntr=0.3,0.1

Type RM Length L Ch R = 1 ,6886    ,157.7,166.9,172.4
XS GIS Cut Line= 4
2242361.71924311460545.9020289642242270.44499934460442.019544475
2242157.95984897460434.1897968482242110.53909188460413.822316959
#Sta/Elev= 30
       0 2312.82    20.5  2311.6    41.3 2311.48    69.6 2310.25    95.1 2309.93
   102.1 2309.18   109.3 2309.13   129.2 2308.15   148.4 2307.92   160.6  2307.2
   164.6 2307.24   172.6 2306.25   188.7 2305.32   196.7 2305.73   200.7 2305.32
   204.7 2305.31   216.7 2304.67220.44232305.438   220.8 2305.51   224.8 2308.65
   232.8 2316.71   236.8 2320.47   248.8  2326.8   261.7  2332.9   270.4 2337.86
   274.5 2339.68   279.1 2340.94   283.5 2342.51   292.8 2346.58   302.7 2351.57
#Mann= 3 ,-1,0
       0      .1       0   204.7    .045       0220.4423      .1       0
#XS Ineff= 2 , 0
          159.47 2318.78
Permanent Ineff=
       F       F
Bank Sta=204.7,220.4423
XS Rating Curve= 0 ,0
Exp/Cntr(USF)=0,0
Exp/Cntr=0.3,0.1

Type RM Length L Ch R = 1 ,6719    ,236.6,238.1,233
XS GIS Cut Line= 3
2242485.11850321460389.1827603062242372.91773666460374.054567063
 2242176.2512245460226.554682947
#Sta/Elev= 30
       0 2347.24    17.1 2339.01    29.2 2332.64    57.7 2313.35    61.5  2311.1
    69.6 2307.35    77.6 2305.28    97.8 2303.99   131.5  2303.9   157.2 2302.68
   171.5 2303.56   180.1 2303.59   189.1 2302.33   200.1 2301.93   204.1 2301.41
   209.1 2300.64   217.2 2300.39   222.9 2300.61   225.8 2301.24   229.1 2302.24
   234.1 2302.62   264.1 2302.12   269.1 2303.44   274.4 2306.69   281.3 2312.62
   294.1 2321.84   299.1 2325.01   314.7 2331.84   328.7 2338.53     359 2354.26
#Mann= 3 ,-1,0
       0      .1       0   204.1    .045       0   225.8      .1       0
#XS Ineff= 2 , 0
           125.9 2312.87   250.2         2313.62
Permanent Ineff=
       F       F
Bank Sta=204.1,225.8
XS Rating Curve= 0 ,0
Exp/Cntr(USF)=0,0
Exp/Cntr=0.3,0.1

Type RM Length L Ch R = 1 ,6481    ,259.7,260.1,258.8
XS GIS Cut Line= 2
 2242574.6269799460227.8153657172242258.19560457460097.965040383
#Sta/Elev= 30
       0  2356.3       7  2352.4    15.6 2349.47    28.6 2341.97    54.5 2328.32
    68.3 2320.34    77.5 2314.24    89.1 2304.86     102 2295.64   106.4 2294.14
   110.7 2294.02   117.3    2296   123.5 2297.32   149.7 2298.07   171.3 2297.19
   179.9 2295.62   188.6 2294.94     194 2295.57   207.1 2295.88   218.8 2297.66
   224.6 2297.92   249.3 2297.94   264.5 2296.89   270.4 2297.48     275  2299.6
   292.3 2314.22     301 2320.27   318.3 2331.23   338.1 2344.62     342 2347.66
#Mann= 3 ,-1,0
       0      .1       0     102    .045       0   117.3      .1       0
#XS Ineff= 2 , 0
                          249.95          2307.5
Permanent Ineff=
       F       F
Bank Sta=102,117.3
XS Rating Curve= 0 ,0
Exp/Cntr(USF)=0,0
Exp/Cntr=0.3,0.1

Type RM Length L Ch R = 1 ,6221    ,140.7,135.2,125.8
XS GIS Cut Line= 3
2242681.78501537459993.3283704542242531.78948126459936.302375882
 2242354.7390186459925.205003314
#Sta/Elev= 30
       0 2343.02    18.8 2335.64    40.2 2326.31    44.5 2324.78    65.9 2315.07
    91.6 2305.18   100.1 2301.11   104.4 2298.44   108.7 2293.78     113 2290.31
   117.3 2289.38   121.5 2289.25   130.1 2290.47   137.8 2291.49   155.8 2291.41
   170.6 2290.84   181.9 2289.84   196.2 2290.18   212.2 2291.37   216.2 2291.36
   236.2 2289.84   248.3 2291.36   252.3 2290.91   256.3 2290.99   268.7 2295.09
   272.2 2296.85   276.4 2299.68   304.4 2314.89   324.4 2327.41   337.9 2336.94
#Mann= 3 ,-1,0
       0      .1       0     113    .045       0   130.1      .1       0
Bank Sta=113,130.1
XS Rating Curve= 0 ,0
Exp/Cntr(USF)=0,0
Exp/Cntr=0.3,0.1

Type RM Length L Ch R = 1 ,6086    ,164.5,170.1,171.8
XS GIS Cut Line= 4
2242699.75937157459813.1693785292242635.34811049459808.995753277
2242528.40430241459836.4395998572242360.42293878459830.955152221
#Sta/Elev= 30
       0 2331.46     7.6 2327.75    47.7 2306.44    67.8 2294.77    76.1 2290.74
    80.2  2289.9   100.9 2289.39   113.2 2290.87   121.5 2289.62     133 2289.09
   140.9 2288.01   149.5 2286.98154.29612288.414   158.7 2289.03   165.9 2288.87
     176 2287.98   191.2 2288.17   207.2 2285.45   215.2 2285.18   219.2 2285.43
   223.2 2287.24   227.2 2287.68   247.2 2287.05   251.2 2287.78   255.2  2290.7
   263.6 2297.83   279.2 2311.76   308.3 2332.94   323.3 2342.92     343 2357.11
#Mann= 3 ,-1,0
       0      .1       0   140.9    .045       0154.2961      .1       0
#XS Ineff= 2 , 0
          111.93 2298.95
Permanent Ineff=
       F       F
Bank Sta=140.9,154.2961
XS Rating Curve= 0 ,0
Exp/Cntr(USF)=0,0
Exp/Cntr=0.3,0.1