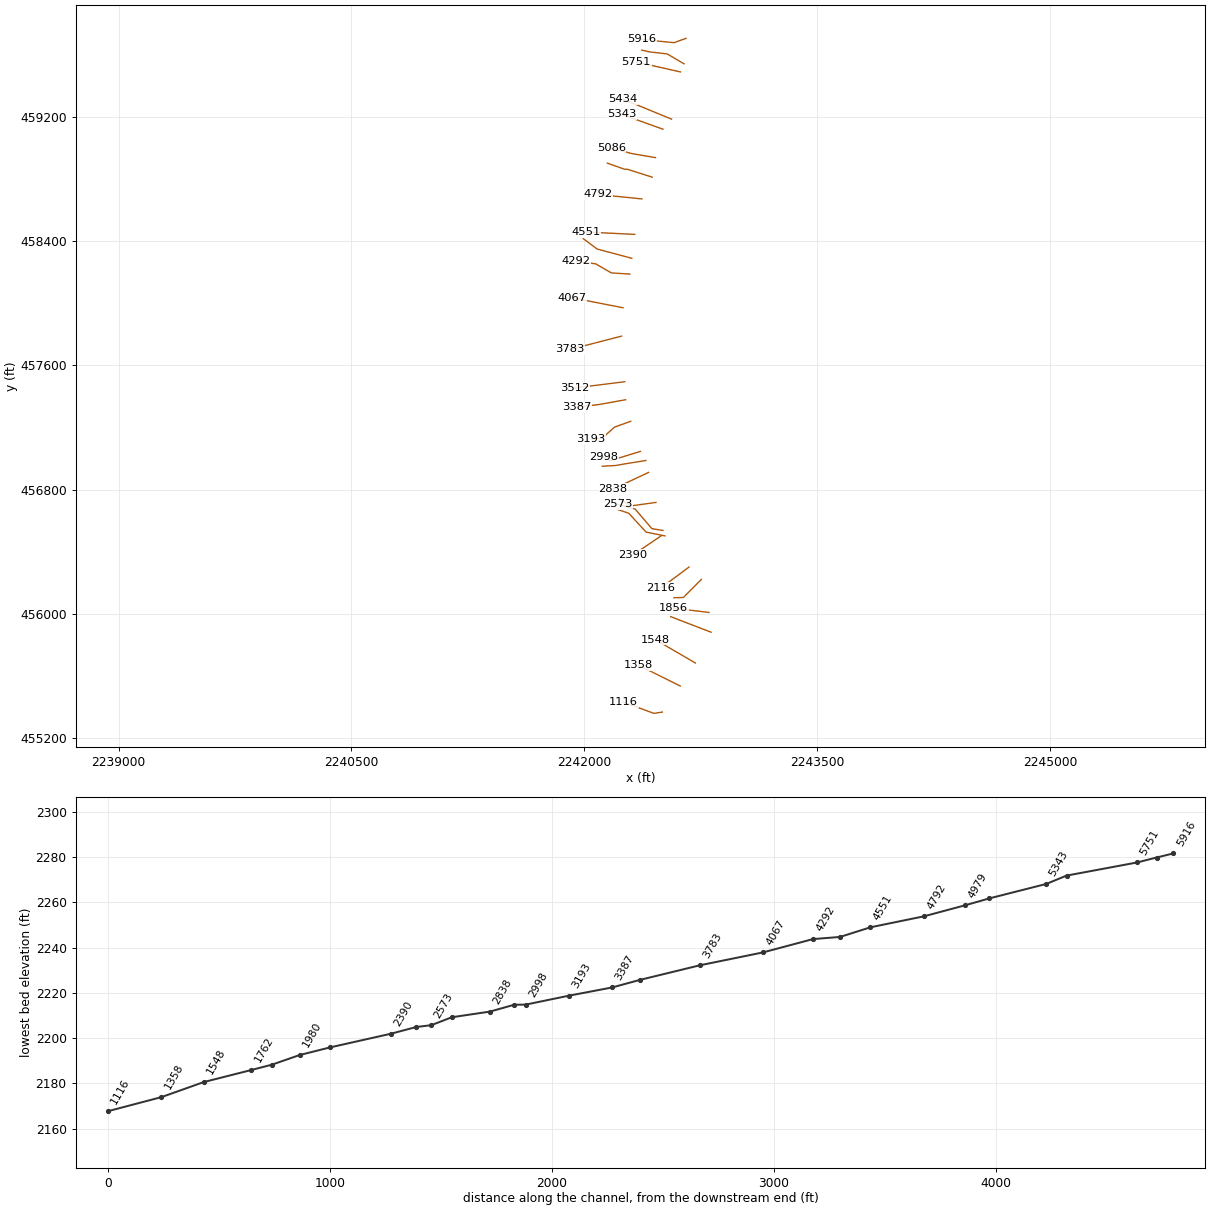
HEC-RAS study LWSLKRN.prj: LWSLKRN

--- LWSLKRN.g01 (geometry) --- (continued)

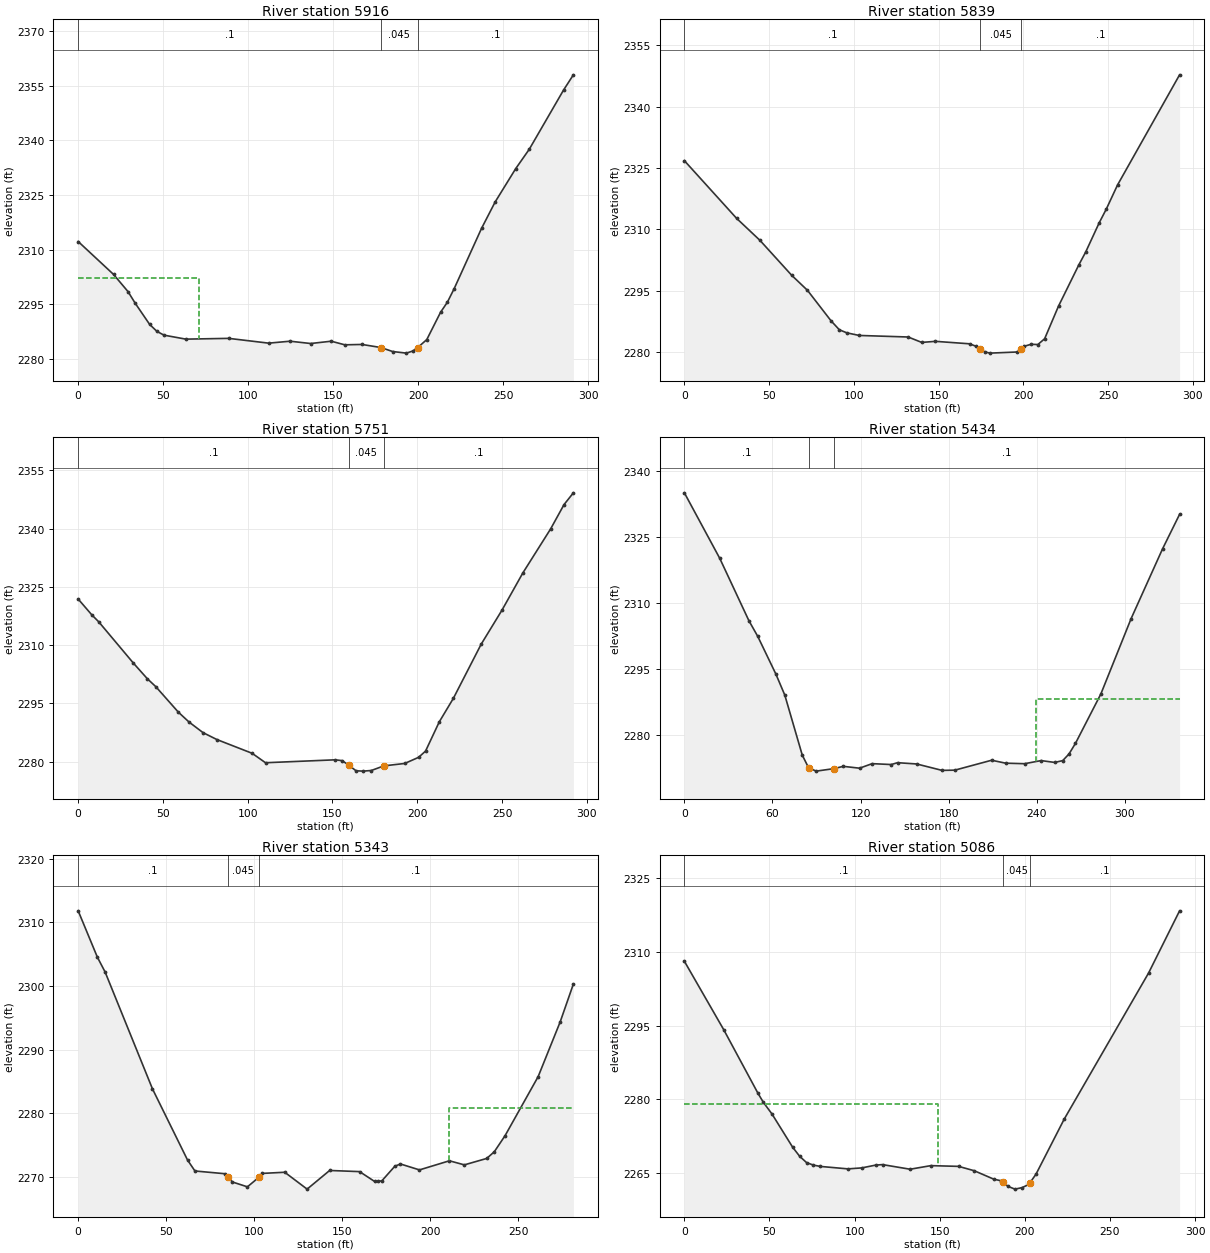
Type RM Length L Ch R = 1 ,5916    ,76.6,76.2,75.7
XS GIS Cut Line= 3
2242655.69519134459706.7879135222242578.36330663459678.798775576
2242370.39637112459699.589284991
#Sta/Elev= 30
       0 2312.23    20.8  2303.2    29.3 2298.49    33.5 2295.32      42  2289.5
    46.3 2287.57    50.5 2286.53    63.3 2285.44    88.5 2285.65     112 2284.34
   124.6 2284.87   136.7 2284.24   148.8 2284.87   156.8 2283.88   166.9 2283.98
178.01332283.138   184.9 2282.04     193  2281.6     197 2282.22   199.7 2283.14
     205 2285.32   213.1 2292.81   217.1 2295.57   221.1 2299.29   237.2 2315.84
   245.2 2323.09   257.3 2332.24   265.3 2337.58   285.4 2353.78   291.2 2357.98
#Mann= 3 ,-1,0
       0      .1       0178.0133    .045       0   199.7      .1       0
#XS Ineff= 2 , 0
           71.26 2302.24
Permanent Ineff=
       F       F
Bank Sta=178.0133,199.7
XS Rating Curve= 0 ,0
Exp/Cntr(USF)=0,0
Exp/Cntr=0.3,0.1

Type RM Length L Ch R = 1 ,5839    ,90,88.1,86.4
XS GIS Cut Line= 4
2242642.73490597459542.5526284812242534.49439787459606.263813628
2242417.34802517459619.9651437682242370.07843619459630.926207879
#Sta/Elev= 30
       0 2326.81    30.8 2312.72    44.6 2307.33    63.3  2298.8    72.6 2295.13
    86.5 2287.68    91.4 2285.49    95.8 2284.74   103.1  2284.1     132 2283.72
     140  2282.4   148.1 2282.66   168.2 2282.06   172.2 2281.43  174.572280.742
   177.2 2280.08   180.3 2279.78   196.4 2280.06   198.8 2280.91   200.4 2281.45
   204.5 2281.94   208.5 2281.88   212.5 2283.29   220.7 2291.28   232.6 2301.29
   236.7 2304.47   244.7 2311.64   248.9    2315   255.5 2320.87   292.1 2347.79
#Mann= 3 ,-1,0
       0      .1       0  174.57    .045       0   198.8      .1       0
Bank Sta=174.57,198.8
XS Rating Curve= 0 ,0
Exp/Cntr(USF)=0,0
Exp/Cntr=0.3,0.1

Type RM Length L Ch R = 1 ,5751    ,318.4,317.3,315.3
XS GIS Cut Line= 2
2242620.01155962459490.3159451332242335.09725355459554.610766415
#Sta/Elev= 30
       0 2321.87       8 2317.82    12.1 2316.02    32.6 2305.37    40.8 2301.36
    45.8 2299.32    59.1 2292.76    65.4 2290.22    73.6 2287.51    81.8 2285.72
   102.6 2282.18   110.5 2279.75   151.6  2280.5   155.7 2280.29   159.5 2279.16
   163.9 2277.68     168 2277.59   172.9 2277.75   180.3 2278.94   192.6 2279.56
   200.8 2281.14   204.9 2282.74     213 2290.27   221.3 2296.31   237.7 2310.24
     250 2319.02   262.3 2328.59   278.7 2339.93   286.6 2346.18   292.1  2349.2
#Mann= 3 ,-1,0
       0      .1       0   159.5    .045       0   180.3      .1       0
Bank Sta=159.5,180.3
XS Rating Curve= 0 ,0
Exp/Cntr(USF)=0,0
Exp/Cntr=0.3,0.1

Type RM Length L Ch R = 1 ,5434    ,90.4,91.5,92
XS GIS Cut Line= 2
2242562.42779674 459186.137772762242250.60720983459314.678819078
#Sta/Elev= 30
       0 2335.11    24.1  2320.2    43.9 2306.05      50 2302.43    62.3 2293.89
    68.4 2289.09    80.3 2275.43    84.6 2272.55    89.8 2271.79   102.1 2272.37
   108.2 2272.88   119.3 2272.46   127.9 2273.49   140.9 2273.29   145.2 2273.71
   158.2 2273.42   175.5 2271.96   184.2 2272.01   209.3 2274.27   218.8  2273.6
   231.7 2273.48     243 2274.19   252.2 2273.77   257.7 2274.18     262  2275.7
   266.4 2278.12   283.7 2289.36   304.3  2306.5   325.7 2322.36   337.3 2330.21
#Mann= 3 ,-1,0
       0      .1       0    84.6    .045       0   102.1      .1       0
#XS Ineff= 2 , 0
                          239.53         2288.27
Permanent Ineff=
       F       F
Bank Sta=84.6,102.1
XS Rating Curve= 0 ,0
Exp/Cntr(USF)=0,0
Exp/Cntr=0.3,0.1

Type RM Length L Ch R = 1 ,5343    ,254.6,256.8,256.4
XS GIS Cut Line= 2
2242506.59217065459121.6240872782242241.90302435459216.512649157
#Sta/Elev= 30
       0 2311.81    10.9 2304.53    15.3  2302.2    42.2 2283.84    62.1 2272.67
    66.3 2270.95    83.3 2270.52   84.832270.057    87.6 2269.22    96.1 2268.46
  102.732269.983   104.6 2270.57   117.3 2270.75     130  2268.1   142.8 2271.03
   159.8 2270.85   168.3 2269.31   170.5 2269.31   172.5 2269.42   179.8 2271.69
     183 2272.05   193.8 2271.12   210.8 2272.55   219.3 2271.91     232 2272.92
   236.3 2273.97   242.4 2276.49   261.2 2285.77   273.7 2294.36   281.2 2300.31
#Mann= 3 ,-1,0
       0      .1       0   84.83    .045       0  102.73      .1       0
#XS Ineff= 2 , 0
                           210.8         2280.78
Permanent Ineff=
       F       F
Bank Sta=84.83,102.73
XS Rating Curve= 0 ,0
Exp/Cntr(USF)=0,0
Exp/Cntr=0.3,0.1

Type RM Length L Ch R = 1 ,5086    ,108.5,107.2,106.1
XS GIS Cut Line= 3
 2242458.9026359458938.318101743 2242306.3499528  458964.3892091
2242174.60003551458998.603954356
#Sta/Elev= 30
       0 2308.08    23.1 2294.16    43.3 2281.17    46.4 2279.37    51.5 2276.98
    63.6 2270.24    67.7  2268.4    71.8  2267.1    75.8  2266.6    79.9 2266.33
    96.1 2265.83   104.2 2266.03   112.4  2266.6   116.4  2266.7   132.6 2265.76
   144.8 2266.49   161.1 2266.34   170.3 2265.45   181.8 2263.73   185.9 2263.42
   187.12263.118   190.2 2262.26   194.2 2261.71   198.3 2262.01   202.5 2262.68
   203.1 2263.04   206.6 2264.78   223.1 2275.94   272.7 2305.69   290.9 2318.34
#Mann= 3 ,-1,0
       0      .1       0   187.1    .045       0   203.1      .1       0
#XS Ineff= 2 , 0
           149.1 2278.94
Permanent Ineff=
       F       F
Bank Sta=187.1,203.1
XS Rating Curve= 0 ,0
Exp/Cntr(USF)=0,0
Exp/Cntr=0.3,0.1

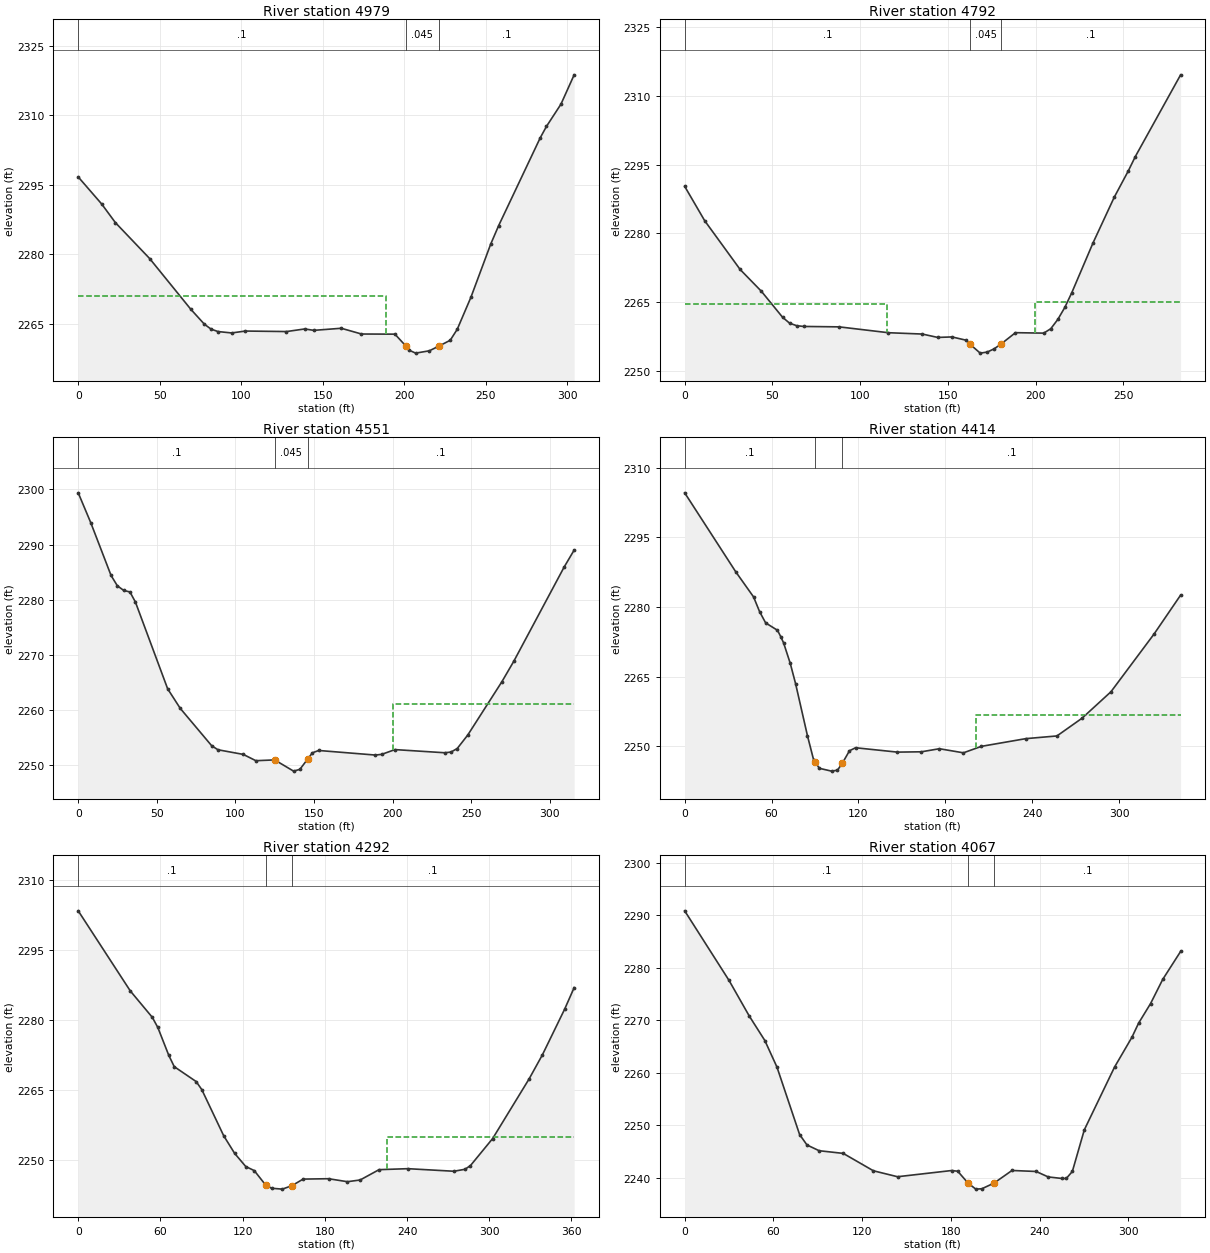
Type RM Length L Ch R = 1 ,4979    ,182.7,186.2,189.7
XS GIS Cut Line= 4
2242437.88111936458812.3443529452242276.48534674458863.718521762
2242260.28514602458863.3663434852242148.51620356458902.837774207
#Sta/Elev= 30
       0 2296.69    14.4 2290.85    22.8 2286.84    43.8  2279.1      69 2268.18
    77.4 2264.93    81.5 2263.88    85.7 2263.36    94.1 2263.06   102.5 2263.47
   127.7 2263.36   138.9 2263.92   144.5 2263.62   161.3 2264.07   173.7 2262.83
   194.2  2262.8200.77132260.292   202.8 2259.36   206.9 2258.71   215.3 2259.21
221.34092260.253   228.1 2261.48   232.4 2263.84   240.8 2270.75   252.9 2282.18
   257.8 2286.19   283.3 2305.12   287.1 2307.57     296 2312.37   304.1  2318.7
#Mann= 3 ,-1,0
       0      .1       0200.7713    .045       0221.3409      .1       0
#XS Ineff= 2 , 0
           188.6 2270.98
Permanent Ineff=
       F       F
Bank Sta=200.7713,221.3409
XS Rating Curve= 0 ,0
Exp/Cntr(USF)=0,0
Exp/Cntr=0.3,0.1

Type RM Length L Ch R = 1 ,4792    ,240.3,241.2,241.9
XS GIS Cut Line= 2
2242371.65705389458672.1328272552242090.52479613 458701.12853097
#Sta/Elev= 30
       0 2290.27    11.4 2282.76    31.6  2272.1    43.7 2267.34    55.8 2261.65
    59.8 2260.36    63.8 2259.82    67.8 2259.65      88 2259.56   116.1 2258.28
   135.4 2257.99   144.2 2257.25   152.3 2257.36   160.3 2256.65   162.72255.725
   168.4 2253.82   172.4 2254.05   176.4 2254.77   180.4 2255.85   188.5 2258.29
   204.6 2258.19   208.6 2259.15   212.6 2261.17   216.6  2263.8   220.6 2267.04
   232.7 2277.92   244.8 2287.91   252.8 2293.65   256.8 2296.79   282.6 2314.64
#Mann= 3 ,-1,0
       0      .1       0   162.7    .045       0   180.4      .1       0
#XS Ineff= 2 , 0
          115.12 2264.51   199.9         2264.89
Permanent Ineff=
       F       F
Bank Sta=162.7,180.4
XS Rating Curve= 0 ,0
Exp/Cntr(USF)=0,0
Exp/Cntr=0.3,0.1

Type RM Length L Ch R = 1 ,4551    ,140.9,137.1,135.5
XS GIS Cut Line= 2
2242325.01179139458443.9492458432242009.84109883458459.077439086
#Sta/Elev= 30
       0 2299.37       8 2293.95    20.9  2284.4    24.9 2282.53      29 2281.68
    32.9 2281.42    36.4 2279.58    56.9 2263.87    64.9 2260.33    84.9 2253.56
    88.9 2252.83     105 2251.99     113 2250.85     125 2250.99     137 2248.96
     141 2249.28  146.222251.238     149 2252.28     153  2252.7   189.1 2251.87
   193.1    2252   201.5 2252.86   233.1 2252.29   237.1 2252.41   241.1 2253.05
   247.8 2255.49   269.5 2265.14   277.1 2268.86   309.2 2285.96   315.5    2289
#Mann= 3 ,-1,0
       0      .1       0     125    .045       0  146.22      .1       0
#XS Ineff= 2 , 0
                          200.45         2261.17
Permanent Ineff=
       F       F
Bank Sta=125,146.22
XS Rating Curve= 0 ,0
Exp/Cntr(USF)=0,0
Exp/Cntr=0.3,0.1

Type RM Length L Ch R = 1 ,4414    ,126.1,121.8,118.7
XS GIS Cut Line= 3
2242306.13354792458289.879574521 2242083.0735885458349.521274902
2241993.61103793458416.319979328
#Sta/Elev= 30
       0 2304.58    35.2 2287.62    47.6 2282.17    51.7 2279.04    55.9  2276.6
    64.1    2275    66.4  2273.6    68.3  2272.3    72.9  2267.9    76.6 2263.51
    84.8  2252.3      89 2247.18      902246.626    93.1  2245.3   101.4  2244.7
   105.5  2244.9   108.8 2246.35   113.8 2249.08     118 2249.73   146.9 2248.79
   163.5 2248.86   175.9 2249.52   192.5 2248.64   204.9 2250.03   235.6 2251.69
   257.1 2252.27   274.4 2256.08   294.4 2261.78   324.2 2274.22   342.5 2282.57
#Mann= 3 ,-1,0
       0      .1       0      90    .045       0   108.8      .1       0
#XS Ineff= 2 , 0
                          201.15         2256.88
Permanent Ineff=
       F       F
Bank Sta=90,108.8
XS Rating Curve= 0 ,0
Exp/Cntr(USF)=0,0
Exp/Cntr=0.3,0.1

Type RM Length L Ch R = 1 ,4292    ,221,225.8,230.2
XS GIS Cut Line= 4
2242294.14476604458188.0355900132242174.56550033 458195.70255269
2242074.06121751458253.8157401932241949.22064631458271.381489695
#Sta/Elev= 30
       0 2303.36      38 2286.21    54.1 2280.54    58.1 2278.38    66.1 2272.41
    70.1 2269.98    86.1 2266.79    90.2 2265.07   106.2 2255.18   114.2  2251.4
   122.3 2248.59   128.5 2247.72136.81582244.628   141.1 2243.94     149 2243.75
156.01482244.496   164.2  2245.9   182.7 2245.98   196.5 2245.34   205.8 2245.71
   219.6 2247.92   240.6 2248.13   274.2 2247.58   282.3    2248   286.3 2248.79
   302.5 2254.58   329.1 2267.35   338.8  2272.5     355 2282.26     362 2286.91
#Mann= 3 ,-1,0
       0      .1       0136.8158    .045       0156.0148      .1       0
#XS Ineff= 2 , 0
                          225.27         2254.89
Permanent Ineff=
       F       F
Bank Sta=136.8158,156.0148
XS Rating Curve= 0 ,0
Exp/Cntr(USF)=0,0
Exp/Cntr=0.3,0.1

Type RM Length L Ch R = 1 ,4067    ,275.6,283.4,289.1
XS GIS Cut Line= 2
2242249.37082518457971.1932070082241920.33262215458035.488028289
#Sta/Elev= 30
       0 2290.81      30 2277.56    43.6 2270.82    54.2 2266.13    62.4 2261.07
    77.7 2248.24    82.7 2246.25    90.9 2245.16   107.2 2244.65   127.6 2241.34
   143.9 2240.21   180.5 2241.39   184.6 2241.26   191.5 2239.03   196.8 2237.85
   200.9 2237.92   209.1 2238.99   221.3  2241.4   237.6 2241.21   245.8 2240.17
     255 2239.88     258 2239.88   262.1 2241.21   270.2 2249.14   290.6 2261.06
   302.4 2266.76   306.9 2269.44     315 2273.17   323.2 2277.76   335.3 2283.08
#Mann= 3 ,-1,0
       0      .1       0   191.5    .045       0   209.1      .1       0
Bank Sta=191.5,209.1
XS Rating Curve= 0 ,0
Exp/Cntr(USF)=0,0
Exp/Cntr=0.3,0.1

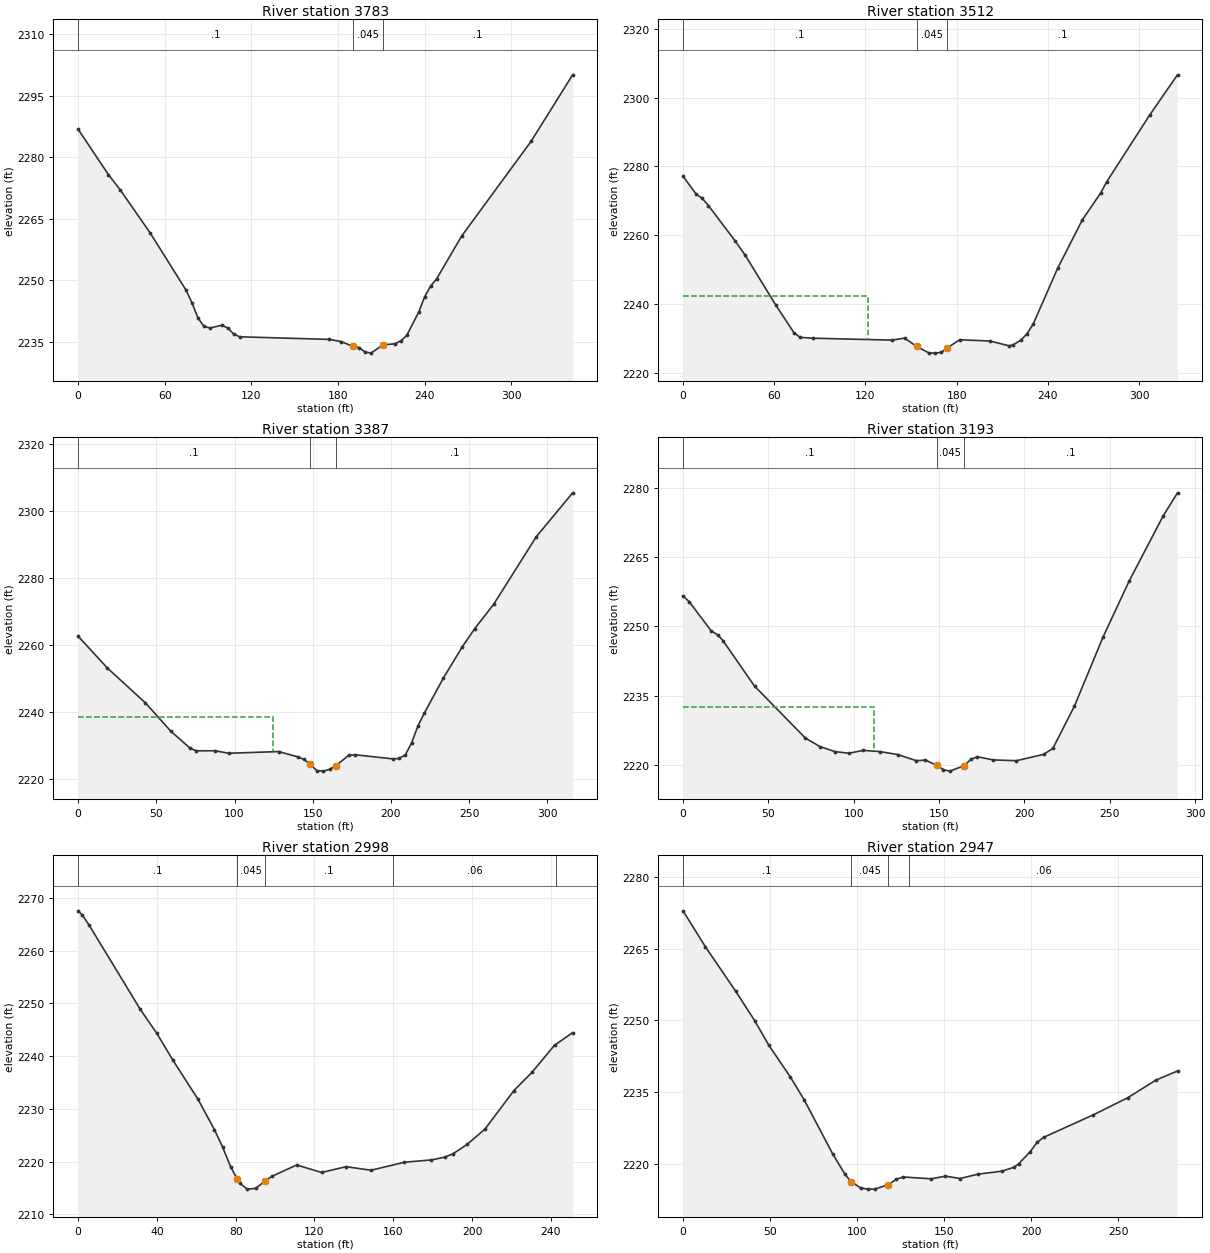
Type RM Length L Ch R = 1 ,3783    ,273.4,271.3,269.5
XS GIS Cut Line= 2
2242240.54604579457788.3942053242241908.98647722457702.667776949
#Sta/Elev= 30
       0 2286.83      21 2275.76    29.3 2271.97      50 2261.47    74.8 2247.53
    78.9 2244.42      83 2240.78    87.1 2238.72    91.3 2238.32    99.5 2238.99
   103.7  2238.3   107.8 2236.83   111.9 2236.17   173.9 2235.53   182.2 2235.01
   190.1 2233.84   194.6 2233.55   198.7 2232.47   202.8 2232.18   211.1 2234.19
   219.6 2234.47   223.5 2235.19   227.6 2236.51   235.9  2242.2     240 2245.94
   244.1 2248.55   248.3 2250.32   265.6 2260.75   313.7 2283.88   342.5 2300.13
#Mann= 3 ,-1,0
       0      .1       0   190.1    .045       0   211.1      .1       0
Bank Sta=190.1,211.1
XS Rating Curve= 0 ,0
Exp/Cntr(USF)=0,0
Exp/Cntr=0.3,0.1

Type RM Length L Ch R = 1 ,3512    ,123.6,124.3,125.1
XS GIS Cut Line= 2
2242260.71697011457494.6551198612241937.98218093457454.313271214
#Sta/Elev= 30
       0 2277.16     8.6    2272    12.6 2270.74    16.7 2268.64    34.1 2258.45
    40.9 2254.19      61 2239.69    73.1 2231.56    77.1 2230.28    85.2 2230.05
   137.6 2229.48   145.7 2230.08   153.7 2227.64   161.8 2225.74   165.8  2225.7
   169.9 2225.94   173.9 2227.22   181.9 2229.59   202.1 2229.22   214.2 2227.84
   216.8 2228.04   222.3 2229.51   226.3 2231.39   230.3 2234.17   246.4 2250.41
   262.6 2264.45   274.7 2272.32   278.7 2275.59   306.9 2294.98   325.2 2306.67
#Mann= 3 ,-1,0
       0      .1       0   153.7    .045       0   173.9      .1       0
#XS Ineff= 2 , 0
          121.51 2242.44
Permanent Ineff=
       F       F
Bank Sta=153.7,173.9
XS Rating Curve= 0 ,0
Exp/Cntr(USF)=0,0
Exp/Cntr=0.3,0.1

Type RM Length L Ch R = 1 ,3387    ,187.3,194,201.5
XS GIS Cut Line= 3
2242266.53415376457378.4516513572242092.38038865457347.437967159
2241954.01164377457331.334708056
#Sta/Elev= 30
       0 2262.61    18.6 2253.17      43 2242.74    59.3 2234.27    71.5 2229.26
    75.5 2228.44    87.7 2228.45    96.2 2227.71   128.3 2228.21   140.5 2226.63
   144.5 2225.85     148 2224.54   152.7 2222.52   156.8 2222.38   160.9 2222.91
   164.9 2224.05     173  2227.1   177.1 2227.26   201.3 2226.03   205.3 2226.16
   209.3 2227.26   213.3 2230.91   217.4 2235.98   221.4 2239.71   233.5 2250.11
   245.6 2259.41   253.6 2264.88   265.7 2272.12     293  2292.3   316.2 2305.36
#Mann= 3 ,-1,0
       0      .1       0     148    .045       0   164.9      .1       0
#XS Ineff= 2 , 0
          124.45 2238.62
Permanent Ineff=
       F       F
Bank Sta=148,164.9
XS Rating Curve= 0 ,0
Exp/Cntr(USF)=0,0
Exp/Cntr=0.3,0.1

Type RM Length L Ch R = 1 ,3193    ,199.4,195.2,189
XS GIS Cut Line= 4
 2242299.6482166457239.6327732792242196.15694731457202.508635234
2242114.47776876457130.3177992652242043.87953363457125.275068184
#Sta/Elev= 30
       0  2256.6     3.7 2255.32    16.4 2249.11    20.7 2248.07    23.4 2246.95
    41.9 2237.12    71.7  2225.9    80.2 2224.06    89.1 2222.97    97.2 2222.63
   105.7 2223.24   115.3 2222.98   125.9 2222.34   136.6 2221.02     142 2221.14
148.60692220.029   152.6 2219.07   156.2 2218.76164.70672219.922   168.6 2221.29
   172.4 2221.88   181.7 2221.18   195.3 2221.01   211.4 2222.39   216.7 2223.68
   229.3 2232.79   246.1 2247.75   261.4 2259.83   281.4 2273.95   289.7 2278.86
#Mann= 3 ,-1,0
       0      .1       0148.6069    .045       0164.7067      .1       0
#XS Ineff= 2 , 0
          112.13 2232.54
Permanent Ineff=
       F       F
Bank Sta=148.6069,164.7067
XS Rating Curve= 0 ,0
Exp/Cntr(USF)=0,0
Exp/Cntr=0.3,0.1

Type RM Length L Ch R = 1 ,2998    ,53.7,51.6,49.7
XS GIS Cut Line= 3
2242362.30083206457045.7762108032242168.57862506456986.355184713
2242126.06602102457009.543877821
#Sta/Elev= 30
       0 2267.57     2.2 2266.74     5.4 2264.96    31.5 2248.92    39.9 2244.37
    48.2  2239.2    60.8 2231.88    69.2 2226.09    73.4 2222.75    77.5 2218.98
    80.8 2216.73    82.2 2215.87    85.9  2214.8    90.1 2214.93      95 2216.36
    98.5 2217.25     111 2219.38   123.6 2217.96   136.1 2219.06   148.7 2218.38
   165.7  2219.9   179.4 2220.34   186.3 2220.87   190.5 2221.54   197.5 2223.27
   206.6  2226.2   221.3 2233.49   230.4 2236.93   241.9 2242.08   251.1 2244.47
#Mann= 5 ,-1,0
       0      .1       0    80.8    .045       0      95      .1       0
     160     .06       0  242.63      .1       0
Bank Sta=80.8,95
XS Rating Curve= 0 ,0
Exp/Cntr(USF)=0,0
Exp/Cntr=0.3,0.1

Type RM Length L Ch R = 1 ,2947    ,105.1,108.9,112.7
XS GIS Cut Line= 4
2242396.87070929456987.1062040332242260.36720194456965.098882697
2242202.72556268456955.0828942032242115.73845153456950.040163122
#Sta/Elev= 30
       0 2272.89    12.9 2265.35    30.2 2256.12    41.2 2249.91    49.3 2244.79
    61.5 2238.25    69.6 2233.38      86 2222.06      93 2217.85 96.42572216.342
     102 2214.99     106 2214.75   110.1 2214.75117.9143  2215.7   122.3 2216.78
   126.3 2217.29   142.5 2216.91   150.6 2217.46   159.1 2216.97   169.5 2217.89
   183.1  2218.5   190.2 2219.35   192.7 2220.04   199.3 2222.55   203.3 2224.55
   207.3 2225.61   235.4 2230.24   255.4 2233.86   271.4 2237.51   283.9 2239.43
#Mann= 4 ,-1,0
       0      .1       0 96.4257    .045       0117.9143      .1       0
     130     .06       0
Bank Sta=96.4257,117.9143
XS Rating Curve= 0 ,0
Exp/Cntr(USF)=0,0
Exp/Cntr=0.3,0.1

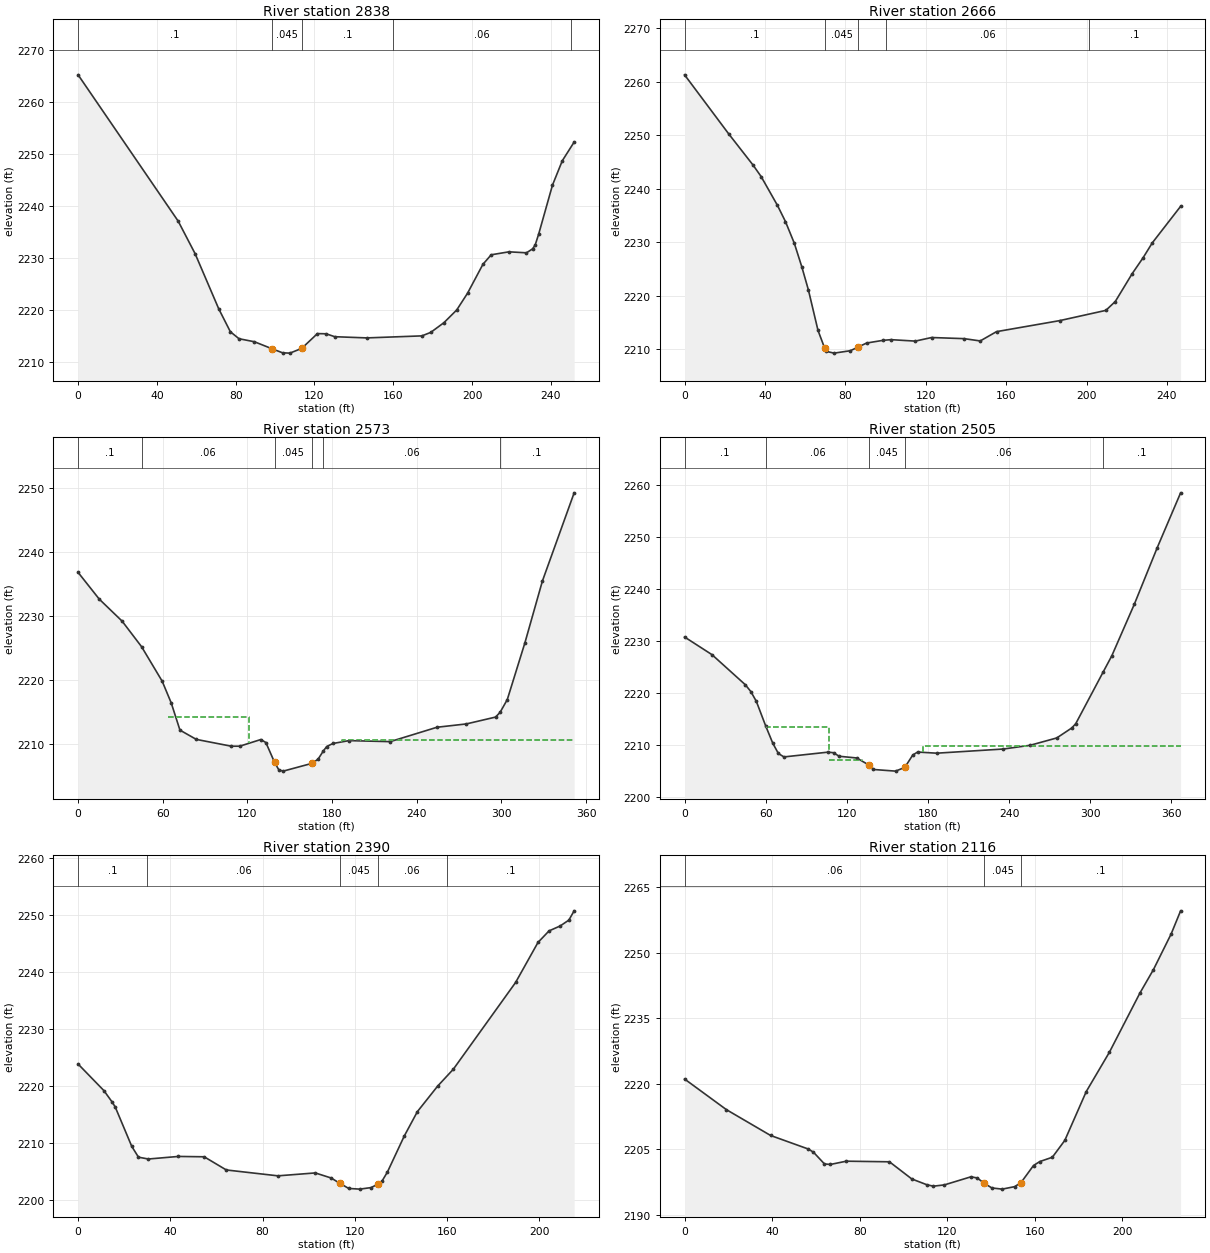
Type RM Length L Ch R = 1 ,2838    ,176.8,172.2,168.8
XS GIS Cut Line= 2
2242414.10909186456910.2650181952242186.28953753456803.088823916
#Sta/Elev= 30
       0 2265.29    50.8 2237.13    59.4 2230.86    71.4 2220.24    77.3 2215.83
    81.7 2214.49    89.5 2213.91    98.42212.568   103.8 2211.78   107.5 2211.72
   113.5 2212.63   121.5 2215.48   125.9 2215.44   130.3 2214.88   146.6 2214.65
   174.5 2215.04     179 2215.71   185.7 2217.58   192.2 2220.03   197.7 2223.26
   205.5 2228.82   209.7 2230.65   218.7 2231.22   227.6 2231.03   230.7 2231.79
     232 2232.51   233.8 2234.64   240.8 2244.06   245.8 2248.76   251.8 2252.35
#Mann= 5 ,-1,0
       0      .1       0    98.4    .045       0   113.5      .1       0
     160     .06       0     250      .1       0
Bank Sta=98.4,113.5
XS Rating Curve= 0 ,0
Exp/Cntr(USF)=0,0
Exp/Cntr=0.3,0.1

Type RM Length L Ch R = 1 ,2666    ,114.7,92.5,79.7
XS GIS Cut Line= 3
2242461.90315252456717.0065005312242302.01770826456694.731432178
2242227.96254797456737.130106528
#Sta/Elev= 30
       0  2261.3    21.9 2250.28    34.1  2244.4    38.1 2242.26    46.2 2236.88
    50.2 2233.84    54.6 2229.79    58.3 2225.41    61.6 2221.07    66.4 2213.46
   69.682210.178    70.4 2209.56    74.4 2209.22    82.5 2209.67    86.5 2210.39
    90.6 2211.11    98.7 2211.61   102.7 2211.74   114.8 2211.47   122.9 2212.14
   139.1 2211.93   147.1  2211.5   155.2 2213.24   186.6  2215.3   209.6 2217.22
   214.3 2218.88   222.7 2224.09   228.1 2227.05   232.7 2229.85   246.8 2236.69
#Mann= 5 ,-1,0
       0      .1       0   69.68    .045       0    86.5      .1       0
     100     .06       0  201.43      .1       0
Bank Sta=69.68,86.5
XS Rating Curve= 0 ,0
Exp/Cntr(USF)=0,0
Exp/Cntr=0.5,0.3

Type RM Length L Ch R = 1 ,2573    ,63.8,67.5,65.4
XS GIS Cut Line= 4
2242507.03751996456536.6281313932242435.73204179456547.864596924
2242328.21849378 456673.806805672242218.53909277456704.063192155
#Sta/Elev= 30
       0 2236.78      15  2232.6    31.2 2229.16      45 2225.16    59.6 2219.77
      66 2216.38    72.2 2212.12    83.8 2210.67   108.5 2209.61   114.6 2209.61
   129.5 2210.65   133.1 2210.18   139.3 2207.06   142.3  2205.9   145.4 2205.71
   165.92206.934   170.1 2207.58   173.8 2208.85   176.2 2209.55   180.6 2210.03
     192 2210.48   221.2 2210.32   254.4 2212.57   275.2 2213.09   295.9 2214.16
   299.1  2214.9   304.2 2216.89   316.7 2225.77   329.1 2235.43   351.6 2249.22
#Mann= 6 ,-1,0
       0      .1       0      45     .06       0   139.3    .045       0
   165.9      .1       0   173.8     .06       0   299.1      .1       0
#XS Ineff= 3 ,-1
   63.75  121.25 2214.18  121.25     126  2209.3     187   351.6 2210.51
Permanent Ineff=
       F       F       F
Bank Sta=139.3,165.9
XS Rating Curve= 0 ,0
Exp/Cntr(USF)=0,0
Exp/Cntr=0.5,0.3

Type RM Length L Ch R = 1 ,2505    ,91.2,115.1,136.7
XS GIS Cut Line= 4
2242520.17556969456501.2194473622242397.94355033456526.033466329
2242286.73998385456647.3464479422242213.21696469456672.160466909
#Sta/Elev= 30
       0  2230.7    20.3  2227.3    44.9 2221.53      49 2220.22    53.1 2218.32
    60.1 2213.54    65.3 2210.25    69.4  2208.3    73.5 2207.64   106.1 2208.56
   110.2 2208.45   114.3 2207.77   127.3 2207.44   136.7 2206.03   139.5 2205.23
   156.1 2204.91   162.9 2205.63   168.8 2208.01   172.4 2208.58   186.5 2208.36
   235.8 2209.16   255.6 2209.88   275.3 2211.29   286.4 2213.21   289.3 2214.02
   309.6 2223.96     316 2227.08   332.6 2236.96   349.6 2247.87   366.9 2258.42
#Mann= 5 ,-1,0
       0      .1       0    60.1     .06       0   136.7    .045       0
   162.9     .06       0   309.6      .1       0
#XS Ineff= 3 ,-1
   60.56  107.17  2213.4  107.17     131 2207.03     176 366.892 2209.66
Permanent Ineff=
       F       F       F
Bank Sta=136.7,162.9
XS Rating Curve= 0 ,0
Exp/Cntr(USF)=0,0
Exp/Cntr=0.5,0.3

Type RM Length L Ch R = 1 ,2390    ,273.6,274.1,274.7
XS GIS Cut Line= 2
2242493.48580138456500.2799152172242315.15210499456379.886135043
#Sta/Elev= 30
       0 2223.85    11.2 2219.19    14.7 2217.23    16.1 2216.33    23.3  2209.4
    26.2 2207.52    30.5  2207.2    43.5 2207.65    54.7 2207.59    64.3 2205.28
    86.7 2204.25   102.9 2204.76   109.8 2203.87113.51342202.946   117.4 2202.04
   122.2 2201.92   127.1 2202.19   129.9 2202.76   131.9 2203.36   134.2 2204.92
   141.5 2211.23   147.2 2215.51     156 2219.99   162.8 2222.95   189.8 2238.15
   199.5 2245.16   204.3 2247.19   209.1 2248.05   212.9 2249.08   215.2 2250.71
#Mann= 5 ,-1,0
       0      .1       0      30     .06       0113.5134    .045       0
   129.9     .06       0     160      .1       0
Bank Sta=113.5134,129.9
XS Rating Curve= 0 ,0
Exp/Cntr(USF)=0,0
Exp/Cntr=0.3,0.1

Type RM Length L Ch R = 1 ,2116    ,134.5,136.7,138.1
XS GIS Cut Line= 2
2242675.49294766456300.8692201522242493.52347524456165.770672446
#Sta/Elev= 30
       0  2221.1    19.1 2214.09    39.3 2208.17    56.5 2205.07    58.9 2204.33
    63.9 2201.65    66.6 2201.53    73.9 2202.28    93.6 2202.14   103.8 2198.21
   110.8 2196.86   113.7 2196.56   118.7 2196.85   130.8  2198.7   133.7 2198.44
  136.872197.211   140.4 2196.15   145.1 2195.88   150.8 2196.45   153.7 2197.38
   159.4 2201.29   162.3  2202.2     168 2203.18   173.7 2207.04   183.5 2218.23
   194.1 2227.26     208 2240.78   214.2 2246.17   222.3 2254.35   226.6 2259.62
#Mann= 3 ,-1,0
       0     .06       0  136.87    .045       0   153.7      .1       0
Bank Sta=136.87,153.7
XS Rating Curve= 0 ,0
Exp/Cntr(USF)=0,0
Exp/Cntr=0.3,0.1

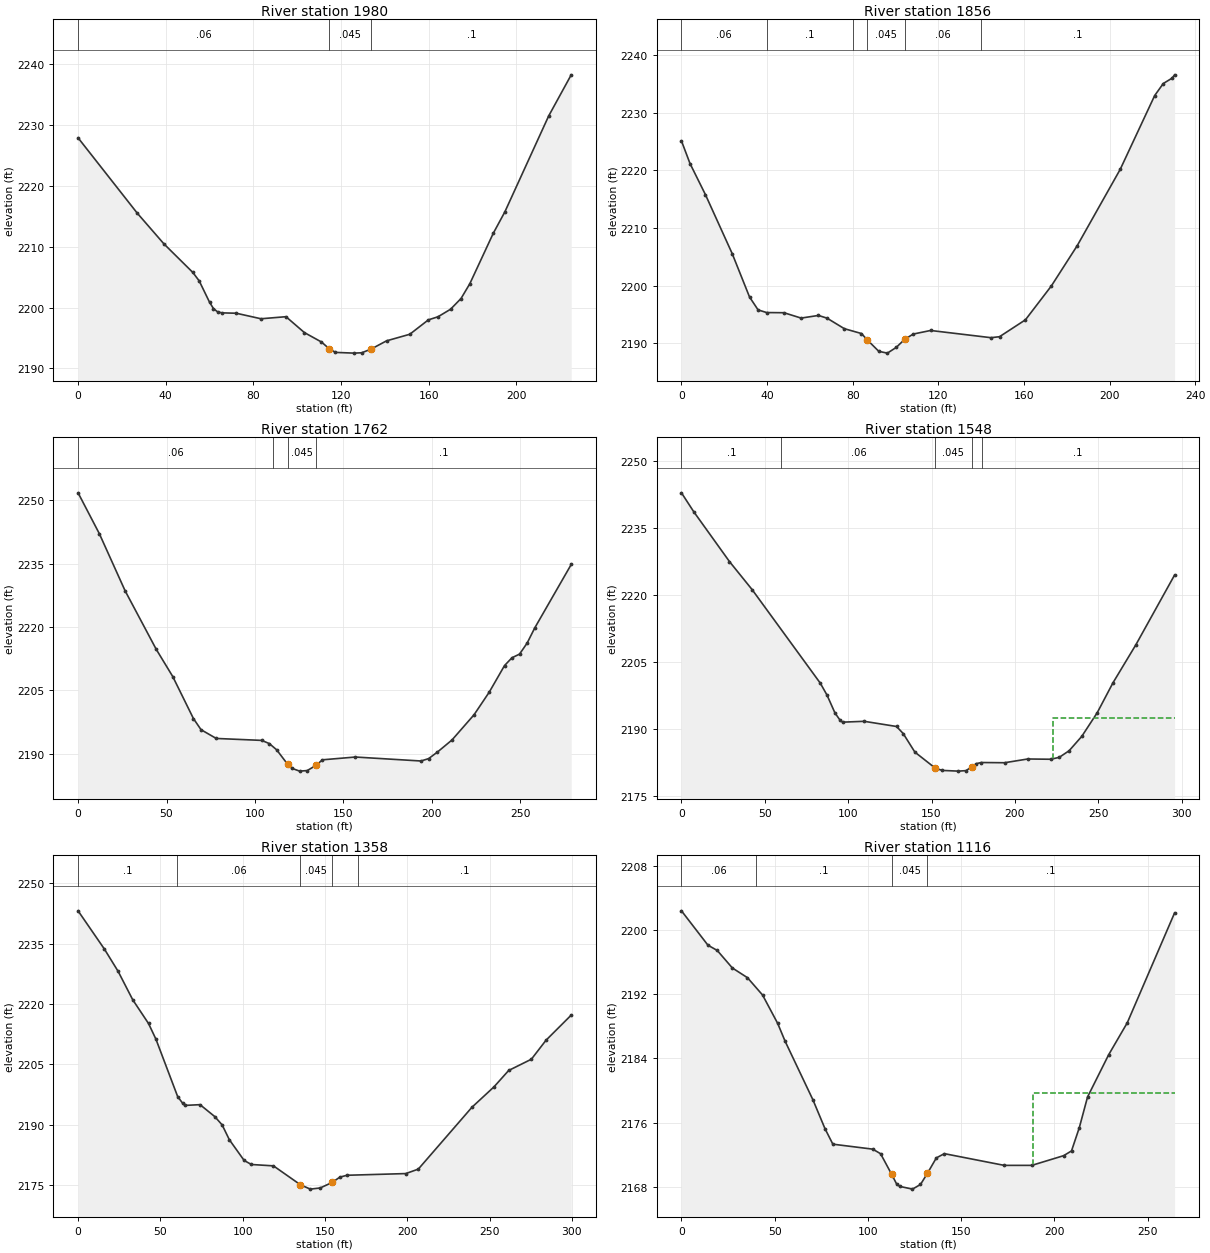
Type RM Length L Ch R = 1 ,1980    ,136.2,124.2,110.5
XS GIS Cut Line= 3
 2242754.5130138456220.9882845372242638.64699436456104.532918801
2242577.84047349456103.157927986
#Sta/Elev= 30
       0 2227.91      27 2215.53    39.2 2210.47    52.4 2205.77    55.3 2204.38
      60 2200.89    61.8 2199.84    63.7 2199.29    65.7 2199.13    72.2 2199.07
    83.5 2198.16    94.9  2198.5   103.3 2195.89   111.1 2194.34   114.7 2193.21
   117.5 2192.63     126 2192.51   129.5 2192.57133.87922193.197   140.8 2194.53
   151.4 2195.61   159.9 2197.98   164.3 2198.49     170 2199.72   174.8 2201.49
   178.8 2203.91   189.5  2212.2   194.8 2215.73   214.8  2231.5   225.1 2238.27
#Mann= 3 ,-1,0
       0     .06       0   114.7    .045       0133.8792      .1       0
Bank Sta=114.7,133.8792
XS Rating Curve= 0 ,0
Exp/Cntr(USF)=0,0
Exp/Cntr=0.3,0.1

Type RM Length L Ch R = 1 ,1856    ,97.4,93.7,91
XS GIS Cut Line= 2
2242803.71990839456008.2722213712242574.94836103456035.646594559
#Sta/Elev= 30
       0 2225.09       4 2221.16    11.2 2215.77    23.7 2205.54    31.8 2198.01
    35.8 2195.77    39.8 2195.31    47.9 2195.28    55.9 2194.35      64 2194.81
      68 2194.34    76.1 2192.51    84.1 2191.67    86.8 2190.57    92.2 2188.58
    96.2 2188.27   100.3 2189.25   104.3 2190.67   108.3 2191.58   116.4  2192.2
   144.6 2190.95   148.6 2191.12   160.7 2194.05   172.8 2199.92   184.9 2206.92
     205 2220.17   221.1 2232.97   225.1 2235.05   229.2 2235.98   230.4 2236.56
#Mann= 6 ,-1,0
       0     .06       0      40      .1       0      80     .06       0
    86.8    .045       0   104.3     .06       0     140      .1       0
Bank Sta=86.8,104.3
XS Rating Curve= 0 ,0
Exp/Cntr(USF)=0,0
Exp/Cntr=0.3,0.1

Type RM Length L Ch R = 1 ,1762    ,215.2,213.5,212.5
XS GIS Cut Line= 2
2242817.02475954455880.8689732022242556.93707927455981.044086807
#Sta/Elev= 30
       0 2251.81      12 2242.15    26.6 2228.59    44.2 2214.72    53.5  2208.3
    65.2 2198.34    69.5  2195.7    78.1 2193.63   103.8 2193.17   108.1 2192.41
   112.2 2190.95   118.5 2187.48   120.9 2186.55   125.2 2185.89   129.5 2186.02
   134.4 2187.23   138.1 2188.57   156.7 2189.23   193.8 2188.29   198.1 2188.85
   203.1 2190.41   211.3 2193.26   223.8 2199.25   232.4 2204.62     241 2210.89
   245.2 2212.74   249.5 2213.61   253.8 2216.23   258.1 2219.82   278.7 2234.84
#Mann= 4 ,-1,0
       0     .06       0     110      .1       0   118.5    .045       0
   134.4      .1       0
Bank Sta=118.5,134.4
XS Rating Curve= 0 ,0
Exp/Cntr(USF)=0,0
Exp/Cntr=0.3,0.1

Type RM Length L Ch R = 1 ,1548    ,189.3,190.6,191.4
XS GIS Cut Line= 2
2242715.61743081455682.6699988532242460.08640595455831.691434696
#Sta/Elev= 30
       0 2242.92     7.3 2238.72    28.8 2227.52    42.4 2221.23    83.3 2200.27
    87.3 2197.61    92.1 2193.59      95 2192.06    96.6 2191.55   109.6 2191.74
     129 2190.58     133    2189     140 2184.84   152.2 2181.26   156.4 2180.74
   166.1 2180.58   170.7 2180.69     174 2181.52   176.9 2182.26   179.9 2182.51
   193.8 2182.46   207.7  2183.3   221.6 2183.24   226.6 2183.67   232.5 2185.14
   240.1 2188.36   249.4 2193.68   258.8 2200.35   272.6 2208.91   295.8 2224.52
#Mann= 5 ,-1,0
       0      .1       0      60     .06       0   152.2    .045       0
     174     .06       0     180      .1       0
#XS Ineff= 2 , 0
                          222.76         2192.46
Permanent Ineff=
       F       F
Bank Sta=152.2,174
XS Rating Curve= 0 ,0
Exp/Cntr(USF)=0,0
Exp/Cntr=0.3,0.1

Type RM Length L Ch R = 1 ,1358    ,239.7,241.6,242.8
XS GIS Cut Line= 2
2242618.51260781455534.3917454122242350.15358788455667.652217639
#Sta/Elev= 30
       0 2243.19      16 2233.67    24.3 2228.15    33.2 2221.06    42.8 2215.15
    47.3 2211.25    60.5 2196.97    63.5 2195.32    65.1 2194.77    74.1 2194.95
      83    2192    87.5 2189.93    91.9 2186.23   100.9 2181.06   105.3 2180.06
   118.7 2179.72   135.1 2175.01   141.1 2173.93   147.1 2174.22   154.5 2175.62
     159 2176.91   163.4 2177.38   199.1  2177.8   206.7 2178.91   239.3 2194.31
   252.7 2199.39   261.6 2203.46   275.4 2206.26   284.3 2210.99   299.6 2217.24
#Mann= 5 ,-1,0
       0      .1       0      60     .06       0   135.1    .045       0
   154.5     .06       0     170      .1       0
Bank Sta=135.1,154.5
XS Rating Curve= 0 ,0
Exp/Cntr(USF)=0,0
Exp/Cntr=0.3,0.1

Type RM Length L Ch R = 1 ,1116    ,33.5,32.5,32.8
XS GIS Cut Line= 3
2242503.14053406455366.3980440062242448.51094735455357.993492204
2242252.40473865455430.832941151
#Sta/Elev= 30
       0 2202.37    14.2 2198.09    19.2 2197.43    27.3 2195.25    35.4 2194.04
    43.5 2191.88    51.6 2188.35    55.6 2186.12    70.5 2178.83      77 2175.22
    81.2  2173.3   102.6 2172.68   106.8 2172.11  112.772169.529   115.4 2168.34
   117.1 2168.04   123.9  2167.7   128.2 2168.28   131.9 2169.66   136.7 2171.59
     141 2172.12   173.1 2170.66   187.9 2170.66     205 2171.87   209.2 2172.46
   213.4 2175.37   217.8 2179.18   229.1 2184.43   239.1 2188.42   264.5 2202.12
#Mann= 4 ,-1,0
       0     .06       0      40      .1       0  112.77    .045       0
   131.9      .1       0
#XS Ineff= 1 ,-1
  188.37264.4689 2179.63
Permanent Ineff=
       F
Bank Sta=112.77,131.9
XS Rating Curve= 0 ,0
Exp/Cntr(USF)=0,0
Exp/Cntr=0.5,0.3