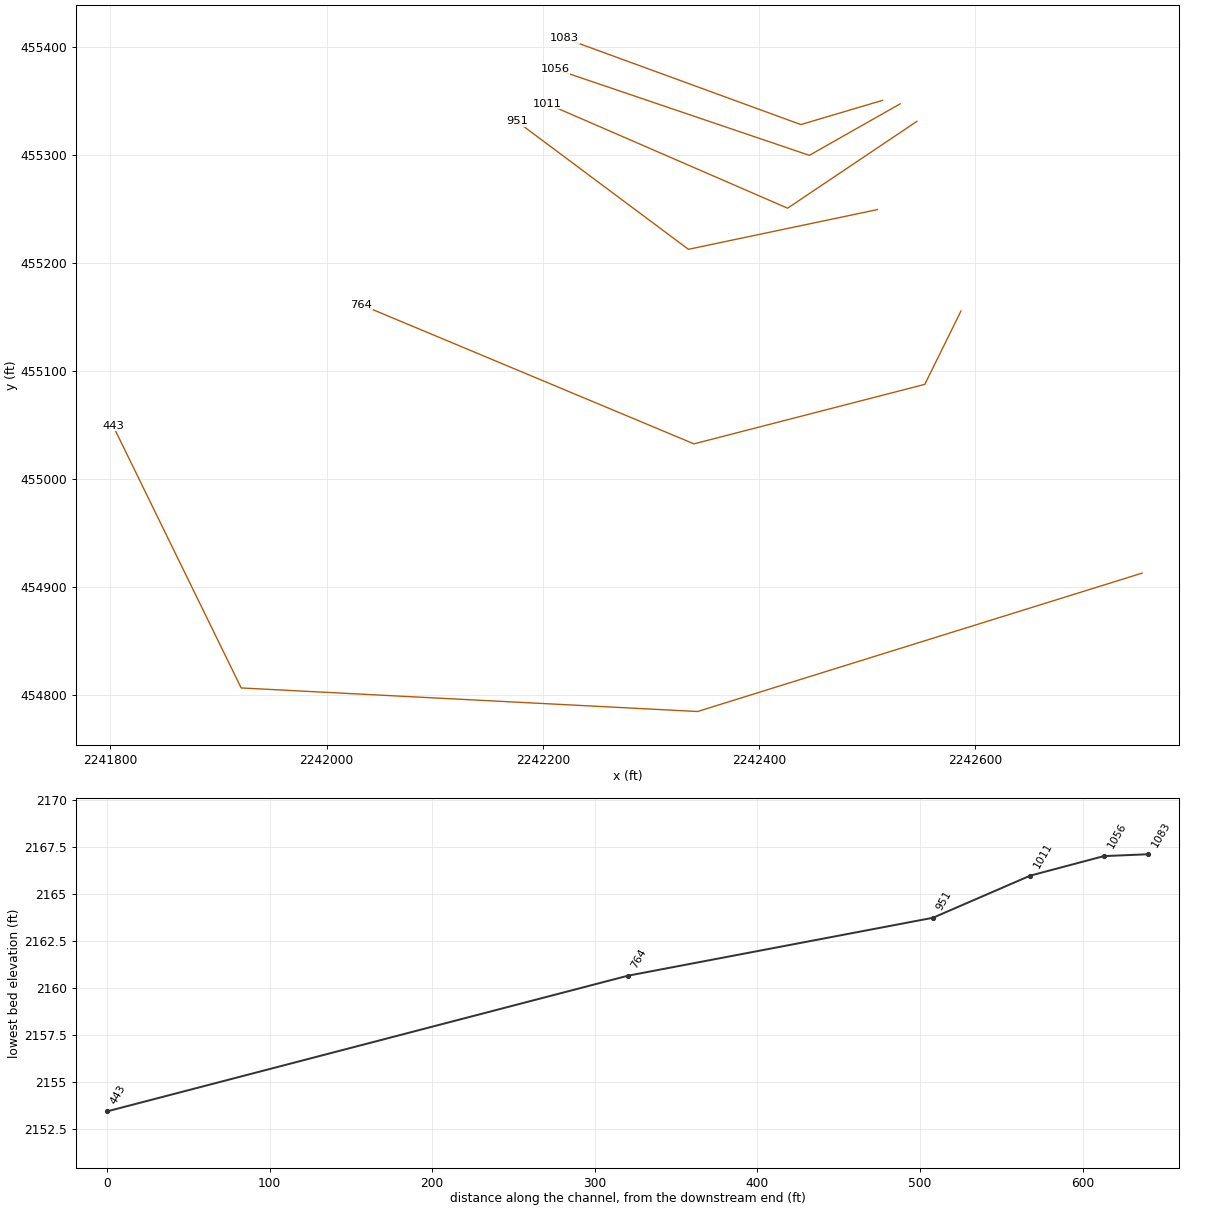
HEC-RAS study LWSLKRN.prj: LWSLKRN

--- LWSLKRN.g01 (geometry) --- (continued)

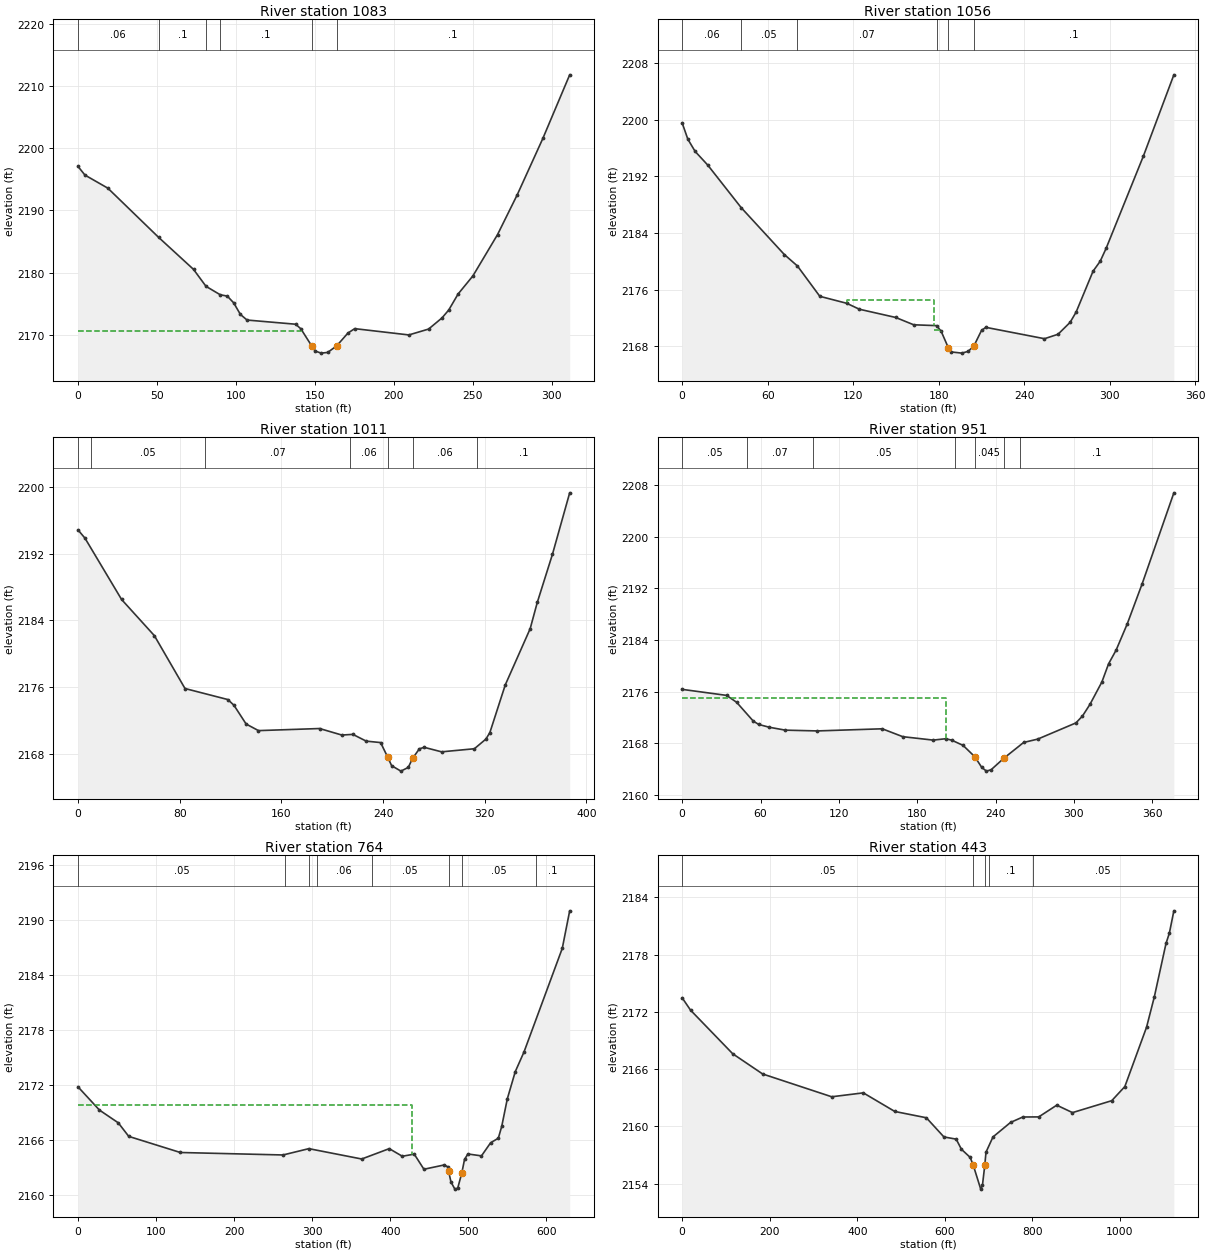
Type RM Length L Ch R = 1 ,1083    ,26.4,27.3,27.3
XS GIS Cut Line= 3
2242514.32276378 455350.420436132242438.68179757455328.008297992
2242220.16345073455407.851540107
#Sta/Elev= 30
       0 2197.07     4.4 2195.68    18.9 2193.58      51  2185.7    73.2 2180.54
    81.1 2177.82    90.1 2176.47    94.6 2176.25    98.6 2175.18   102.9 2173.31
   107.1 2172.41   137.9 2171.74   141.2    2171  148.112168.238   150.4 2167.43
     154  2167.1   158.2 2167.21   163.9 2168.27     171 2170.32   175.3 2171.03
   209.6 2170.02   222.1 2170.96   230.6 2172.75   234.9 2174.03   240.8 2176.59
   250.2  2179.5   265.8 2186.13   278.3 2192.53   294.5 2201.56   311.5 2211.77
#Mann= 6 ,-1,0
       0     .06       0      51      .1       0    81.1     .07       0
    90.1      .1       0  148.11    .045       0   163.9      .1       0
#XS Ineff= 2 , 0
             142 2170.72     179         2170.75
Permanent Ineff=
       F       F
Bank Sta=148.11,163.9
XS Rating Curve= 0 ,0
Exp/Cntr(USF)=0,0
Exp/Cntr=0.5,0.3

Type RM Length L Ch R = 1 ,1056    ,46.7,45.3,44.8
XS GIS Cut Line= 3
2242530.58644382455347.168852691 2242446.5409258455299.543059149
2242211.21347536455379.386301264
#Sta/Elev= 30
       0 2199.57       4 2197.26     9.1 2195.54    17.9 2193.62    41.4 2187.59
    71.7 2180.95    80.9 2179.33    96.6 2175.04   115.5 2174.05   124.4 2173.21
   149.8 2172.05   162.5 2171.01   178.6 2170.89   181.8 2170.08  186.762167.783
   188.8 2167.17   196.3    2167   200.7 2167.25   204.7    2168   210.1 2170.21
   213.1 2170.65   254.3 2169.04   263.8 2169.67   272.3 2171.36   276.5 2172.81
   288.4  2178.6   293.4    2180   297.6 2181.85   323.7 2194.88   345.1 2206.38
#Mann= 6 ,-1,0
       0     .06       0    41.4     .05       0    80.9     .07       0
   178.6     .06       0  186.76    .045       0   204.7      .1       0
#XS Ineff= 3 ,-1
   115.7  176.74 2174.51  176.74     182 2170.25     213 345.105 2170.25
Permanent Ineff=
       F       F       F
Bank Sta=186.76,204.7
XS Rating Curve= 0 ,0
Exp/Cntr(USF)=0,0
Exp/Cntr=0.5,0.3

Type RM Length L Ch R = 1 ,1011    ,63.7,59.8,56.9
XS GIS Cut Line= 3
2242546.04246748455330.9766906892242426.43256007455250.659543056
2242203.71193733455347.311888773
#Sta/Elev= 30
       0 2194.84     5.5 2193.85    34.3 2186.51    60.1 2182.18    84.2 2175.85
   117.9 2174.53   122.7 2173.85   132.3  2171.6     142 2170.81   190.1 2171.06
   207.6 2170.28   216.3 2170.36   226.8 2169.55   238.1 2169.38   243.7 2167.63
   246.8 2166.61   254.1 2165.96   259.9 2166.41   263.3 2167.49   268.6 2168.63
   272.4 2168.81   286.1 2168.27   311.9 2168.64     321  2169.8   324.1 2170.58
   336.2 2176.28   355.8 2183.01   361.4 2186.16   373.3  2191.9   386.9 2199.28
#Mann= 7 ,-1,0
       0     .06       0      10     .05       0     100     .07       0
  214.07     .06       0   243.7    .045       0   263.3     .06       0
  314.07      .1       0
Bank Sta=243.7,263.3
XS Rating Curve= 0 ,0
Exp/Cntr(USF)=0,0
Exp/Cntr=0.3,0.1

Type RM Length L Ch R = 1 ,951     ,184.6,187.5,190.7
XS GIS Cut Line= 3
2242509.43948449 455249.349104312242334.68802344455212.617484085
2242176.02966831455330.950986054
#Sta/Elev= 30
       0 2176.37      34 2175.44    41.7 2174.37    54.4 2171.47    58.6 2170.94
    66.7 2170.51      79 2170.06   103.5 2169.94   153.2 2170.27   168.9 2169.05
   192.2 2168.52   201.7 2168.73   206.3 2168.52   215.1  2167.7   224.12165.942
   229.4 2164.29     233 2163.72   236.6 2163.94   246.4 2165.73   261.5 2168.16
   272.2 2168.67   301.5 2171.18   306.5 2172.24   312.2 2174.03   321.4 2177.52
   326.5 2180.32   332.3 2182.45   340.8  2186.5   352.3 2192.75   376.5 2206.78
#Mann= 7 ,-1,0
       0     .05       0      50     .07       0     100     .05       0
  208.57     .06       0   224.1    .045       0   246.4     .06       0
  258.57      .1       0
#XS Ineff= 2 , 0
          202.39 2175.07
Permanent Ineff=
       F       F
Bank Sta=224.1,246.4
XS Rating Curve= 0 ,0
Exp/Cntr(USF)=0,0
Exp/Cntr=0.3,0.1

Type RM Length L Ch R = 1 ,764     ,314.8,320.5,325.5
XS GIS Cut Line= 4
2242586.75719142455155.4563736372242553.33790122455087.702795853
2242339.83612054455032.6675070532242031.84485222455161.389538636
#Sta/Elev= 30
       0 2171.81    27.5 2169.27    51.6 2167.88      65  2166.4   131.1 2164.64
   262.6 2164.37   295.7 2165.06   363.4 2163.93   398.7 2165.06   415.4 2164.23
   430.7 2164.46   443.1 2162.81   469.1 2163.28   473.4 2163.09474.65192162.613
   477.7 2161.43   482.7 2160.64   486.4 2160.75491.65192162.419   495.1 2163.88
   499.4 2164.48   516.8 2164.27   528.5  2165.7   538.4  2166.2   542.8 2167.51
   549.9  2170.5   560.1 2173.47   571.3 2175.62   620.3 2186.93   629.8 2191.03
#Mann= 8 ,-1,0
       0     .05       0  265.55     .06       0  295.55     .05       0
  306.03     .06       0  376.03     .05       0474.6519    .045       0
491.6519     .05       0  586.03      .1       0
#XS Ineff= 2 , 0
          428.09  2169.8
Permanent Ineff=
       F       F
Bank Sta=474.6519,491.6519
XS Rating Curve= 0 ,0
Exp/Cntr(USF)=0,0
Exp/Cntr=0.3,0.1

Type RM Length L Ch R = 1 ,443     ,,,
XS GIS Cut Line= 4
2242754.37915861454913.1038169442242343.13035842454785.099223509
2241920.98755029454806.8872394132241802.51521381455049.278916342
#Sta/Elev= 30
       0 2173.47    19.1 2172.18   115.4 2167.61   183.8 2165.49   341.6  2163.1
   413.8 2163.51   485.7 2161.56   557.8  2160.9   597.9 2158.89   625.9 2158.66
   637.9  2157.6     658 2156.74   665.1  2155.9     682 2153.42     686 2153.85
   691.4 2155.98     694 2157.29     710 2158.89   750.1 2160.41   778.1 2160.98
   814.5 2160.99   855.7 2162.22   891.6 2161.44   981.3 2162.69  1011.2 2164.17
  1060.8 2170.39  1078.6 2173.58  1105.3 2179.18  1112.9 2180.25  1123.2 2182.59
#Mann= 5 ,-1,0
       0     .05       0   665.1    .045       0   691.4     .05       0
  700.71      .1       0  800.71     .05       0
Bank Sta=665.1,691.4
XS Rating Curve= 0 ,0
Exp/Cntr(USF)=0,0
Exp/Cntr=0.3,0.1
LCMann Table=0

Chan Stop Cuts=-1
Use User Specified Reach Order=0
Composite Channel Slope=5